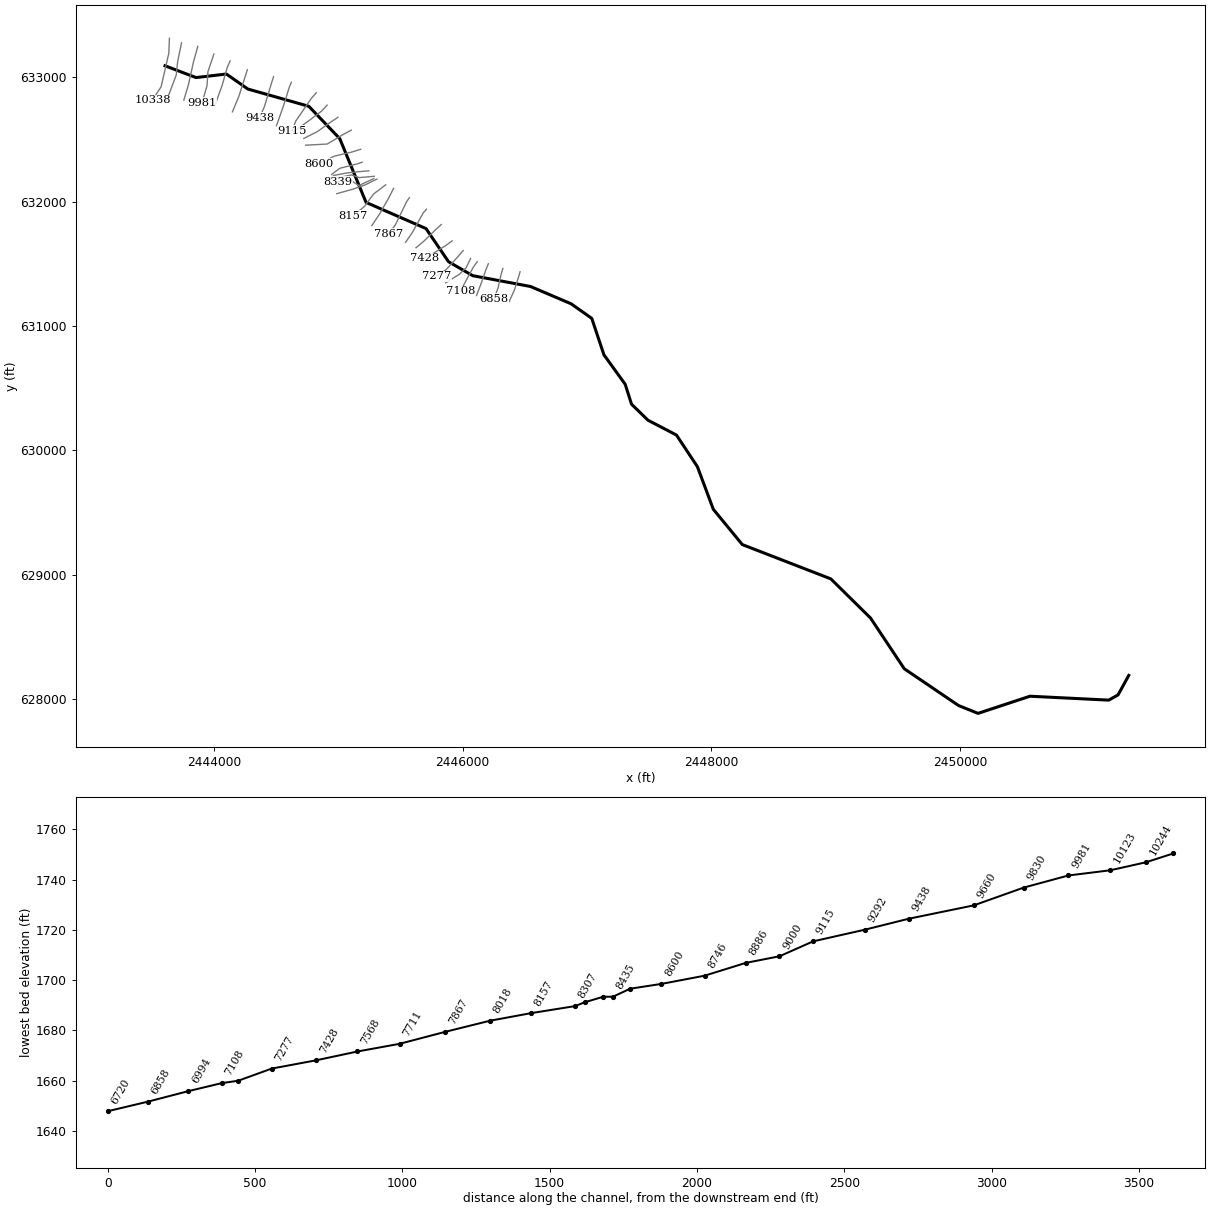
--- HAMMERRN.prj (project) ---

Proj Title=HAMMERRN
Current Plan=p01
Default Exp/Contr=0,0
English Units
Geom File=g01
Flow File=f01
Plan File=p01
Background Map Layer=QC
BEGIN DESCRIPTION:
Stream Name:Hammer Run
Flood Zone: Zone A
Pendleton County, WV
WVDHSEM Flood Warning & Analysis Mapping
HEC-RAS Version: 5.0.7
Hydrology Method:
Regression
Model Notes:
Tie in with South Branch Potomac River at the downstream end.
END DESCRIPTION:
DSS Export Rating Curves= 0
DSS Export Rating Curve Sorted= 0
DSS Export Volume Flow Curves= 0
DXF OffsetX= 0
DXF OffsetY= 0
DXF ScaleX= 0
DXF ScaleY= 0

--- HAMMERRN.p01 (plan) ---

Plan Title=Floodplain
Program Version=5.07
Short Identifier=Floodplain
Geom File=g01
Flow File=f01
Subcritical Flow
K Sum by GR= 0
Std Step Tol= 0.01
Critical Tol= 0.01
Num of Std Step Trials= 20
Max Error Tol= 0.3
Flow Tol Ratio= 0.001
Split Flow NTrial= 30
Split Flow Tol= 0.02
Split Flow Ratio= 0.02
Log Output Level= 0
Friction Slope Method= 1
Unsteady Friction Slope Method= 2
Unsteady Bridges Friction Slope Method= 1
Parabolic Critical Depth
Global Vel Dist= 0 , 0 , 0
Global Log Level= 0
CheckData=True
Encroach Param=-1 ,0,0, 0
Mapping Interval=1HOUR
Computation Time Step Use Courant=        0
Computation Time Step Use Time Series=    0
Computation Time Step Count To Double=0
Computation Time Step Max Doubling=0
Computation Time Step Max Halving=0
Computation Time Step Residence Courant=0
Run HTab= 0
Run UNet= 0
Run Sediment= 0
Run PostProcess= 0
Run WQNet= 0
Run RASMapper= 0
UNET Theta= 0
UNET Theta Warmup= 0
UNET ZTol= 0
UNET ZSATol= 0
UNET MxIter= 0
UNET Max Iter WO Improvement= 0
UNET MaxInSteps= 0
UNET DtIC= 0
UNET DtMin= 0
UNET MaxCRTS= 0
UNET WFStab= 0
UNET SFStab= 0
UNET WFX= 1
UNET SFX= 1
UNET 1D Methodology=Finite Difference
UNET DSS MLevel= 1
UNET Pardiso=0
UNET DZMax Abort= 0
UNET Use Existing IB Tables= 0
UNET Froude Reduction=False
UNET Froude Limit= 0
UNET Froude Power= 0
UNET D1 Cores= 0
UNET D2 Coriolis=0
UNET D2 Cores= 0
UNET D2 Theta= 1
UNET D2 Theta Warmup= 1
UNET D2 Z Tol= 0.01
UNET D2 Volume Tol= 0.01
UNET D2 Max Iterations= 20
UNET D2 Equation= 0
UNET D2 RampUpFraction=0.1
UNET D2 TimeSlices= 1
UNET D2 BCVolumeCheck=0
UNET D1D2 MaxIter= 0
UNET D1D2 ZTol=0.01
UNET D1D2 QTol=0.1
UNET D1D2 MinQTol=1
Write IC File= 0
Write IC File at Fixed DateTime=0
Write IC File at Sim End=0
Echo Input=False
Echo Parameters=False
Echo Output=False
Write Detailed= 0
HDF Write Warmup=0
HDF Write Time Slices=0
HDF Flush=0
HDF Face Node Velocities=0
HDF Compression= 1
HDF Chunk Size= 1
HDF Spatial Parts= 1
HDF Use Max Rows=0
HDF Fixed Rows= 1
Calibration Method= 0
Calibration Iterations= 20
Calibration Max Change=0.05
Calibration Tolerance=0.2
Calibration Maximum=1.5
Calibration Minimum=0.5
Calibration Optimization Method= 1
WQ AD Non Conservative
WQ ULTIMATE=-1
WQ Max Comp Step=1HOUR
WQ Output Interval=15MIN
WQ Output Selected Increments= 0
WQ Output face flow=0
WQ Output face velocity=0
WQ Output face area=0
WQ Output face dispersion=0
WQ Output cell volume=0
WQ Output cell surface area=0
WQ Output cell continuity=0
WQ Output cumulative cell continuity=0
WQ Output face conc=0
WQ Output face dconc_dx=0
WQ Output face courant=0
WQ Output face peclet=0
WQ Output face adv mass=0
WQ Output face disp mass=0
WQ Output cell mass=0
WQ Output cell source sink temp=0
WQ Output nsm pathways=0
WQ Output nsm derived pathways=0
WQ Output MaxMinRange=-1
WQ Daily Max Min Mean=-1
WQ Daily Range=0
WQ Daily Time=0
WQ Create Restart=0
WQ Fixed Restart=0
WQ System Summary=0
WQ Write To DSS=0
WQ Use Fixed Temperature=0
Sorting and Armoring Iterations= 10
XS Update Threshold= 0.02
Bed Roughness Predictor= 0
Hydraulics Update Threshold= 0.02
Energy Slope Method= 1
Volume Change Method= 1
Sediment Retention Method= 0
XS Weighting Method= 0
Number of US Weighted Cross Sections= 1
Number of DS Weighted Cross Sections= 1
Upstream XS Weight=0
Main XS Weight=1
Downstream XS Weight=0
Number of DS XS's Weighted with US Boundary= 1
Upstream Boundary Weight= 1
Weight of XSs Associated with US Boundary= 0
Number of US XS's Weighted with DS Boundary= 1
Downstream Boundary Weight= 0.5
Weight of XSs Associated with DS Boundary= 0.5
Percentile Method= 0
Sediment Output Level= 3
Mass or Volume Output= 0
Output Increment Type= 1
Profile and TS Output Increment= 1
XS Output Flag= 0
XS Output Increment= 10
Write Gradation File= 0
Read Gradation Hotstart= 0
Write HDF5 File= 1
Write Binary Output= 1
Write DSS Sediment File= 0
SV Curve= 0
Specific Gage Flag= 0

--- HAMMERRN.f01 (steady flow) ---

Flow Title=Flows
Program Version=5.07
Number of Profiles= 6
Profile Names=P100yr,P10yr,P25yr,P50yr,P500yr,P101yr
River Rch & RM=HAMMERRN,Main            ,10338
     590     276     390     487     866     719
River Rch & RM=HAMMERRN,Main            ,7711
     659     307     435     544     968     802
River Rch & RM=HAMMERRN,Main            ,6858
     870     404     573     717    1281    1059
River Rch & RM=HAMMERRN,Main            ,4458
    1015     471     668     836    1497    1236
River Rch & RM=HAMMERRN,Main            ,3824
    1368     631     898    1126    2023    1665
Boundary for River Rch & Prof#=HAMMERRN,Main            , 1
Up Type= 0
Dn Type= 3
Dn Slope=0.01518
Boundary for River Rch & Prof#=HAMMERRN,Main            , 2
Up Type= 0
Dn Type= 3
Dn Slope=0.01518
Boundary for River Rch & Prof#=HAMMERRN,Main            , 3
Up Type= 0
Dn Type= 3
Dn Slope=0.01518
Boundary for River Rch & Prof#=HAMMERRN,Main            , 4
Up Type= 0
Dn Type= 3
Dn Slope=0.01518
Boundary for River Rch & Prof#=HAMMERRN,Main            , 5
Up Type= 0
Dn Type= 3
Dn Slope=0.01518
Boundary for River Rch & Prof#=HAMMERRN,Main            , 6
Up Type= 0
Dn Type= 3
Dn Slope=0.01518
DSS Import GetInterval= 0
DSS Import GetPeak= 0
DSS Import FillOption= 0

--- HAMMERRN.g01 (geometry) ---

Geom Title=Geometry
Program Version=5.07

River Reach=HAMMERRN        ,Main
Reach XY= 30
     2443606.597      633093.204     2443855.557       632998.31
     2444100.004      633026.806     2444272.546      632906.238
     2444763.101      632767.309     2445012.121      632507.055
     2445223.471      631994.292     2445706.017      631783.592
     2445886.963      631517.049     2446081.662      631404.767
     2446546.667      631317.669     2446873.905      631178.212
     2447039.297      631061.187     2447137.004      630768.273
     2447308.226      630530.868     2447359.113       630371.01
     2447491.621      630241.922     2447720.505      630122.727
     2447888.894      629868.357     2448016.992      629525.461
     2448250.279      629241.579     2448962.327      628965.796
     2449281.705      628650.833      2449552.94      628242.909
     2449989.201      627947.283     2450146.478      627883.844
     2450564.405      628021.836     2451197.571      627990.375
 2451272.6855063628032.3900879062451358.94085082628189.040084088

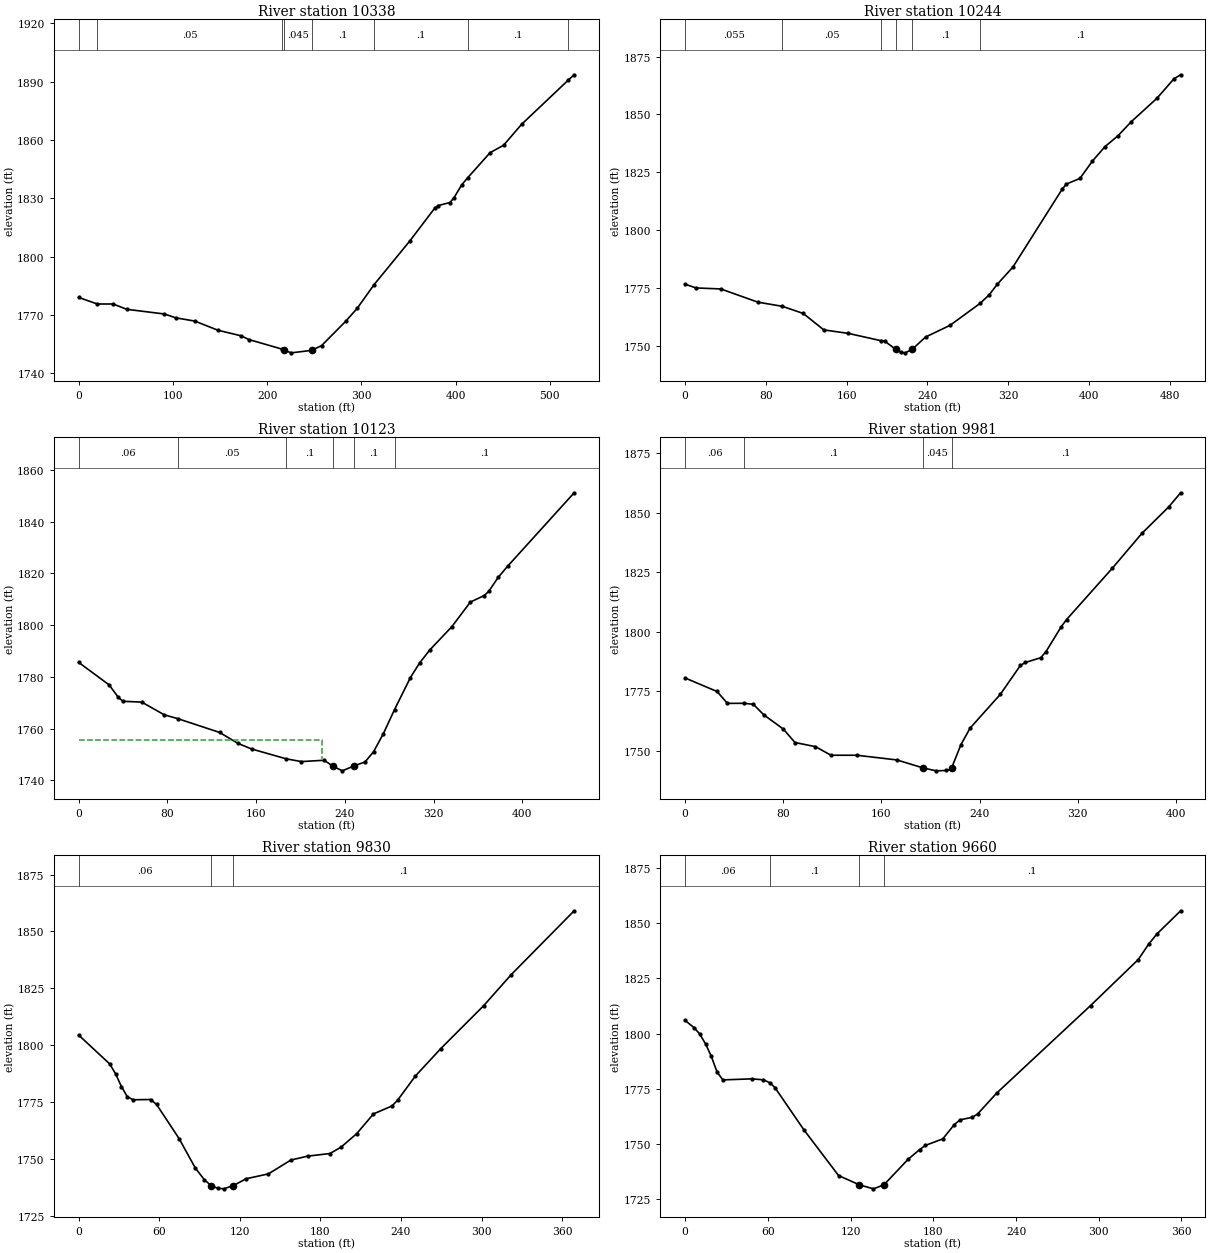
Type RM Length L Ch R = 1 ,10338   ,92,93.6,94.4
XS GIS Cut Line= 4
 2443641.8518131633313.9267678432443636.70747019633193.034709658
2443574.97535538632924.2427930532443504.24064048632816.211592121
#Sta/Elev= 30
       0 1778.96   19.861775.591    36.6 1775.59    51.1 1772.85    91.1 1770.44
   103.1 1768.46   123.2 1766.81   147.8 1762.09   172.5  1759.2   180.7 1757.29
   215.81752.375  217.97 1751.73   225.8 1750.45  247.37 1751.73   257.9 1754.19
   283.3 1766.62   295.6 1773.33  313.591785.573   351.4 1807.97   377.7 1824.77
   381.8 1826.28   394.1 1827.81   398.4 1830.31   406.6 1836.93  412.761840.472
   436.7 1853.48     451 1857.29   470.1 1868.05  519.851890.907525.9196 1893.56
#Mann= 8 ,-1 , 0
       0     .06       0   19.86     .05       0   215.8      .1       0
  217.97    .045       0  247.37      .1       0  313.59      .1       0
  412.76      .1       0  519.85      .1       0
Bank Sta=217.97,247.37
XS Rating Curve= 0 ,0
Exp/Cntr(USF)=0,0
Exp/Cntr=0.3,0.1

Type RM Length L Ch R = 1 ,10244   ,122.8,121.4,121.1
XS GIS Cut Line= 4
2443738.92227255633277.5593154112443707.98290826633125.675163415
2443696.73223033633018.7937231212443616.10237187632805.030842534
#Sta/Elev= 30
       0 1776.57    10.9 1774.97    35.4 1774.53    72.1 1768.82   96.341767.024
     117 1763.95   137.4 1756.83   161.8 1755.31  193.991752.171     198 1751.86
  208.651748.444   214.1 1747.08   218.1 1746.91  225.051748.443   238.2 1753.74
   262.4 1758.78  292.241768.281   301.2 1771.96   309.4 1776.61   324.8 1784.01
   373.5 1817.62   377.8 1819.89   391.2 1822.32   403.4 1829.75     416 1836.06
   429.1 1840.85   441.9 1846.79   467.6 1857.02   484.3 1865.39490.9392 1867.13
#Mann= 6 ,-1 , 0
       0    .055       0   96.34     .05       0  193.99      .1       0
  208.65    .045       0  225.05      .1       0  292.24      .1       0
Bank Sta=208.65,225.05
XS Rating Curve= 0 ,0
Exp/Cntr(USF)=0,0
Exp/Cntr=0.3,0.1

Type RM Length L Ch R = 1 ,10123   ,139.6,141.4,143
XS GIS Cut Line= 4
2443870.18018169633249.4326205972443834.55303492633120.049824452
2443795.17566218 632941.914090632443757.67340243632817.219076954
#Sta/Elev= 30
       0 1785.61    27.5 1776.91    35.8 1772.09      40 1770.57    56.9 1770.27
    77.3 1765.34   89.181763.904   127.1 1758.55   143.6 1754.34   155.9 1752.17
  187.111748.367   200.9 1747.29   221.4 1747.81  228.991745.589   237.8 1743.72
  248.081745.589   258.3 1747.16   265.9 1751.06   274.7 1757.99  284.841767.355
   299.2 1779.76   307.4 1785.33   316.6 1790.38   336.5 1799.37   353.2 1808.88
   365.7 1811.41   369.9 1813.08   378.3 1818.43   386.8 1822.72446.8468  1851.1
#Mann= 6 ,-1 , 0
       0     .06       0   89.18     .05       0  187.11      .1       0
  228.99    .045       0  248.08      .1       0  284.84      .1       0
#XS Ineff= 2 , 0
          219.61 1755.51
Permanent Ineff=
       F       F
Bank Sta=228.99,248.08
XS Rating Curve= 0 ,0
Exp/Cntr(USF)=0,0
Exp/Cntr=0.3,0.1

Type RM Length L Ch R = 1 ,9981    ,154.1,151.3,153
XS GIS Cut Line= 4
2443999.56297783633187.5538920062443951.74759665633045.982861442
 2443944.2471447632932.5385256912443904.86977196632797.530390584
#Sta/Elev= 30
       0 1780.67      26    1775    34.5    1770   48.011770.032    55.6 1769.63
      64 1765.24    80.1 1759.19    89.5 1753.57   106.2 1751.83   118.9 1748.22
     140 1748.22   172.6 1746.24   194.11742.864   204.6 1741.67   212.7 1741.82
   216.7 1742.31  217.13 1742.86   224.7 1752.61   232.2 1759.61   256.8 1773.78
   273.2 1785.93   277.3 1787.19   289.8 1789.18     294 1791.71   306.5 1802.22
   310.8 1805.21   348.2 1826.82   372.1 1841.35     394 1852.49403.7533 1858.45
#Mann= 4 ,-1 , 0
       0     .06       0   48.01      .1       0   194.1    .045       0
  217.13      .1       0
Bank Sta=194.1,217.13
XS Rating Curve= 0 ,0
Exp/Cntr(USF)=0,0
Exp/Cntr=0.3,0.1

Type RM Length L Ch R = 1 ,9830    ,170.2,169.8,171.2
XS GIS Cut Line= 4
2444129.88333047633132.2380588722444105.50686163 633075.04711275
2444066.12948889632936.2887516672444010.81365576632783.467043177
#Sta/Elev= 30
       0 1804.46    23.2 1791.72    27.6  1787.3    31.9 1781.78    36.2 1777.38
    40.6 1776.01    53.6 1776.12      58 1773.96    74.8 1758.94    86.9 1745.97
    93.7 1740.81   98.561738.316   103.4 1737.15   108.1 1736.86  115.271738.316
   124.7 1741.29   141.3 1743.44     158 1749.51   170.4 1751.22   187.1 1752.38
   195.4 1755.19     207 1761.11   219.5 1769.79   233.4 1773.32   237.7 1775.99
   250.7 1786.44   269.5 1798.43   301.5 1817.33   322.1 1831.04368.9316 1859.08
#Mann= 3 ,-1 , 0
       0     .06       0   98.56    .045       0  115.27      .1       0
Bank Sta=98.56,115.27
XS Rating Curve= 0 ,0
Exp/Cntr(USF)=0,0
Exp/Cntr=0.3,0.1

Type RM Length L Ch R = 1 ,9660    ,221.5,221.6,221.4
XS GIS Cut Line= 4
2444268.64169155633060.9837653432444248.95300518633000.042593245
  2444201.137624632849.0959977432444148.63446035 632722.52587108
#Sta/Elev= 30
       0 1805.97     6.4 1802.78    10.6 1799.85    14.8 1795.42      19 1789.77
    23.2 1782.57    27.4 1779.08    48.4 1779.54    56.8 1779.12   61.851777.656
    65.3 1775.47    86.2 1756.45   111.3 1735.79  126.43 1731.58   136.6 1729.77
   144.21731.578   161.8 1743.18   170.1 1747.52   174.3 1749.44   186.9 1752.38
   195.3 1758.88   199.5 1761.01   207.9 1762.09   212.1  1763.6   225.9 1773.05
   294.1 1812.72   328.7 1833.55   336.1 1840.41   342.2 1845.11359.4092 1855.61
#Mann= 4 ,-1 , 0
       0     .06       0   61.85      .1       0  126.43    .045       0
   144.2      .1       0
Bank Sta=126.43,144.2
XS Rating Curve= 0 ,0
Exp/Cntr(USF)=0,0
Exp/Cntr=0.3,0.1

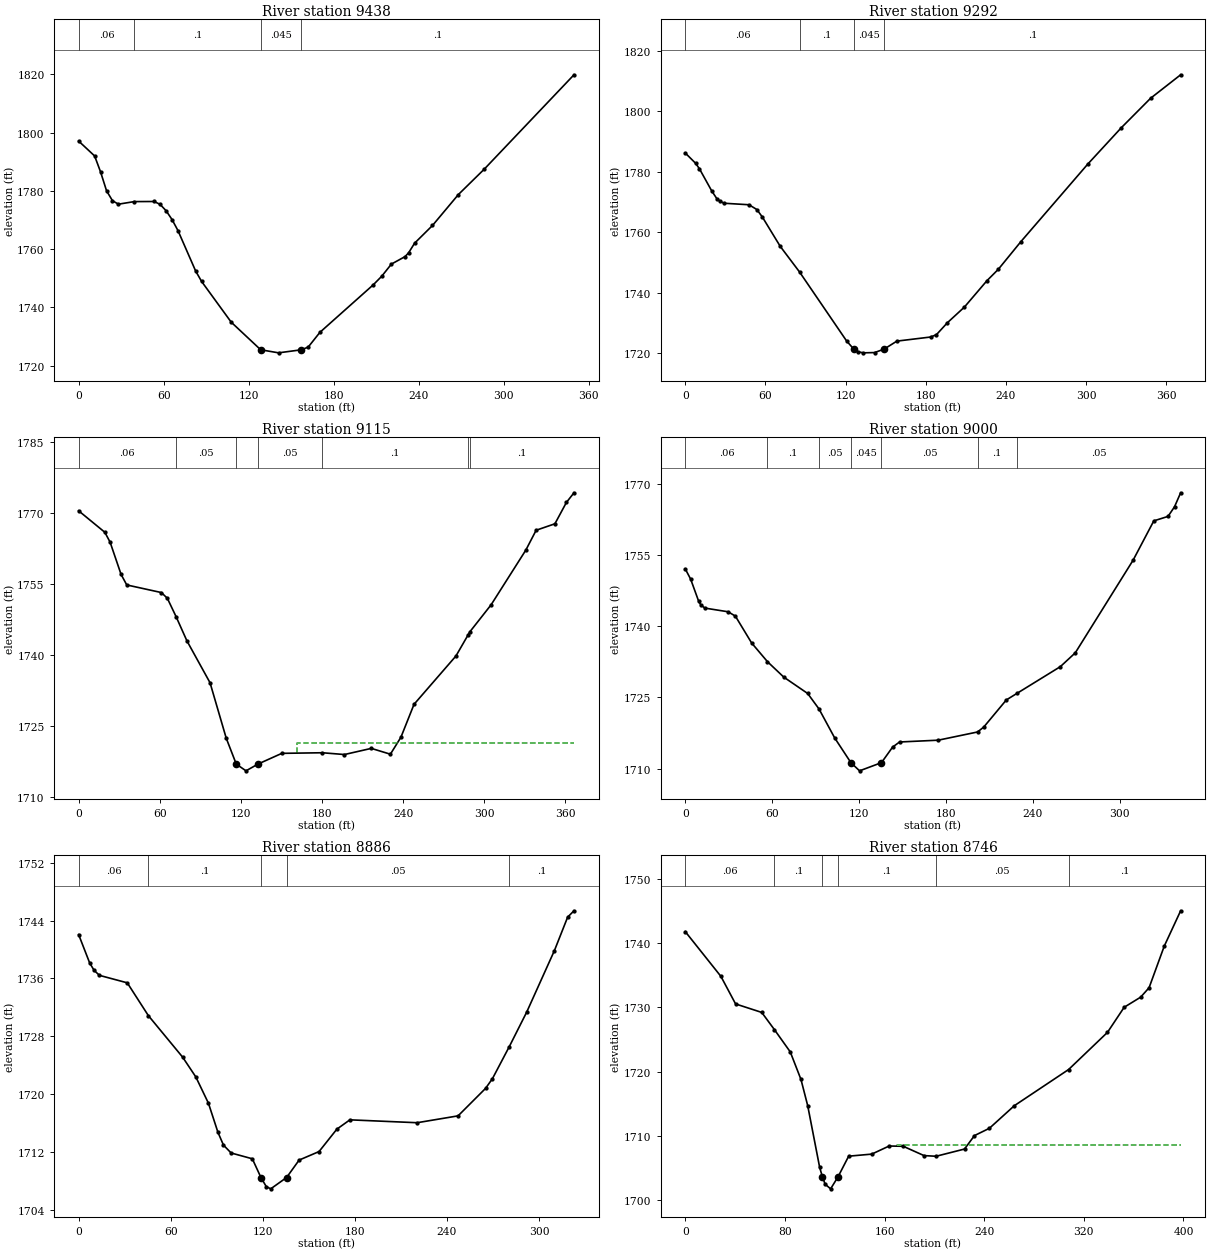
Type RM Length L Ch R = 1 ,9438    ,146.2,146.3,146
XS GIS Cut Line= 4
2444479.59190266633005.6679322082444461.77832928632950.352099074
2444405.52493965632762.8408003132444366.14756691 632675.64804639
#Sta/Elev= 30
       0  1797.1    11.3 1791.98    15.5 1786.49    19.7 1780.04    23.9 1776.62
    28.1 1775.44   39.281776.323    53.3 1776.36    57.5 1775.37    61.7  1773.2
    65.9 1770.18    70.1 1766.38    82.6 1752.48    86.8 1748.91   107.7 1734.94
  128.471725.483   141.1 1724.43  157.221725.481     162 1726.41   170.3 1731.48
   207.9 1747.77   213.9 1750.72   220.7 1754.88   230.4 1757.47   232.9 1758.79
   237.1 1762.07   249.7 1768.13     268 1778.76   286.2 1787.44 349.553 1819.84
#Mann= 4 ,-1 , 0
       0     .06       0   39.28      .1       0  128.47    .045       0
  157.22      .1       0
Bank Sta=128.47,157.22
XS Rating Curve= 0 ,0
Exp/Cntr(USF)=0,0
Exp/Cntr=0.3,0.1

Type RM Length L Ch R = 1 ,9292    ,180.6,177.3,175.1
XS GIS Cut Line= 4
2444623.03804621632960.6652205062444608.03714231632925.975630235
2444560.22176113632774.091478239  2444503.030815632610.019091823
#Sta/Elev= 30
       0 1786.22     7.7 1782.84    10.6 1781.01    19.8 1773.68    23.7 1771.07
    25.9  1770.3      29 1769.61    47.7 1769.11    53.6 1767.52    57.8 1764.98
    71.1 1755.34   85.531746.879   120.7  1724.1  126.091721.384   129.1 1720.49
   133.3 1720.14   141.7 1720.23  148.871721.382   158.4 1724.02   183.6 1725.37
     188 1726.15   196.2  1730.1   208.9 1735.26   225.8    1744   234.3 1747.76
   251.2 1756.91   301.2 1782.52   326.3 1794.55   348.3 1804.33370.7813 1812.09
#Mann= 4 ,-1 , 0
       0     .06       0   85.53      .1       0  126.09    .045       0
  148.87      .1       0
Bank Sta=126.09,148.87
XS Rating Curve= 0 ,0
Exp/Cntr(USF)=0,0
Exp/Cntr=0.3,0.1

Type RM Length L Ch R = 1 ,9115    ,117.5,114.3,111.4
XS GIS Cut Line= 4
2444823.67513588632876.2851360632444784.29776314632832.219980855
2444658.66519298632649.3964645632444627.72582868 632569.70416259
#Sta/Elev= 30
       0 1770.47    19.4 1765.92    23.3 1763.82    31.4 1757.01    35.6 1754.78
    61.2 1753.17    65.6 1751.97   72.091748.074    80.1 1742.95    97.2 1734.09
   109.2 1722.34   116.6 1716.88   123.8 1715.45  132.65 1716.88   150.3 1719.15
   180.31719.277   196.6  1718.9   216.5  1720.2   230.6 1718.97   238.4 1722.56
   248.1 1729.53   279.1 1739.75  287.92 1744.13  289.511744.911   305.1 1750.58
   330.8 1762.16   338.4 1766.35   352.3 1767.72   360.8 1772.24 366.412 1774.28
#Mann= 7 ,-1 , 0
       0     .06       0   72.09     .05       0   116.6    .045       0
  132.65     .05       0   180.3      .1       0  287.92     .05       0
  289.51      .1       0
#XS Ineff= 2 , 0
                          161.87         1721.24
Permanent Ineff=
       F       F
Bank Sta=116.6,132.65
XS Rating Curve= 0 ,0
Exp/Cntr(USF)=0,0
Exp/Cntr=0.3,0.1

Type RM Length L Ch R = 1 ,9000    ,114.2,114.2,113.8
XS GIS Cut Line= 4
2444909.93033331 632776.90414772 2444866.8027346632729.088766536
 2444760.8588508632649.3964645632444643.66428907632564.078823627
#Sta/Elev= 30
       0 1752.06     3.7 1749.92     9.3  1745.2    10.7  1744.5    13.5 1743.81
    29.6 1743.03    34.6 1742.11    45.8 1736.46   56.75 1732.51      68 1729.26
    84.5 1725.81    92.31722.553   103.1 1716.46  114.311711.238   120.3 1709.51
  135.44 1711.24   143.1 1714.51   147.9 1715.59   174.6 1715.97  201.721717.698
     206 1718.73   221.6 1724.45  228.881725.823   258.9 1731.47   269.2 1734.38
   309.1  1753.9   323.4 1762.19   333.2 1763.13   337.7 1765.16341.9233 1768.11
#Mann= 7 ,-1 , 0
       0     .06       0   56.75      .1       0    92.3     .05       0
  114.31    .045       0  135.44     .05       0  201.72      .1       0
  228.88     .05       0
Bank Sta=114.31,135.44
XS Rating Curve= 0 ,0
Exp/Cntr(USF)=0,0
Exp/Cntr=0.3,0.1

Type RM Length L Ch R = 1 ,8886    ,141.9,140.3,141.9
XS GIS Cut Line= 4
2444997.12308724632678.460715871 2444926.8063502632631.582891181
2444833.98825732632565.0163801212444723.35659105632508.762990493
#Sta/Elev= 30
       0 1742.07     7.2 1738.14    10.1 1737.11    13.6 1736.42    31.7 1735.39
   45.431730.856    67.8  1725.1    76.4 1722.36    84.6 1718.73    90.8  1714.7
    94.4 1712.93    99.4 1711.84   113.2 1711.04  118.821708.446   122.3 1707.19
   125.2 1706.88  135.531708.446   143.7 1710.86   156.7 1712.04   168.3 1715.14
   176.8 1716.43   220.6 1716.03   247.3 1716.98   265.2 1720.78   269.7 1722.13
  280.661726.556     292 1731.33   310.1 1739.86   318.7 1744.48322.8427 1745.36
#Mann= 5 ,-1 , 0
       0     .06       0   45.43      .1       0  118.82    .045       0
  135.53     .05       0  280.66      .1       0
Bank Sta=118.82,135.53
XS Rating Curve= 0 ,0
Exp/Cntr(USF)=0,0
Exp/Cntr=0.3,0.1

Type RM Length L Ch R = 1 ,8746    ,148.3,146.1,143.7
XS GIS Cut Line= 4
2445104.94208403632575.3295015532445036.50045998632538.764798294
 2444911.8054463 632463.760278792444737.41993845632454.384713852
#Sta/Elev= 30
       0 1741.78    28.6 1734.82    40.4 1730.53    61.4 1729.21   71.551726.539
    84.3 1723.07    92.9 1718.78    98.3 1714.71   107.9 1705.11  110.121703.633
   112.3 1702.49   116.7 1701.77  122.641703.633   131.2 1706.85   149.7 1707.17
   163.7 1708.43     175 1708.39   191.7 1706.94   201.41706.838   224.2 1707.96
   232.2 1710.05   244.2 1711.19   264.2  1714.7  307.791720.329     339 1726.11
   352.4 1730.01   365.6 1731.58   372.4 1733.05   384.6 1739.53397.7487 1745.02
#Mann= 6 ,-1 , 0
       0     .06       0   71.55      .1       0  110.12    .045       0
  122.64      .1       0   201.4     .05       0  307.79      .1       0
#XS Ineff= 2 , 0
                          169.89         1708.65
Permanent Ineff=
       F       F
Bank Sta=110.12,122.64
XS Rating Curve= 0 ,0
Exp/Cntr(USF)=0,0
Exp/Cntr=0.3,0.1

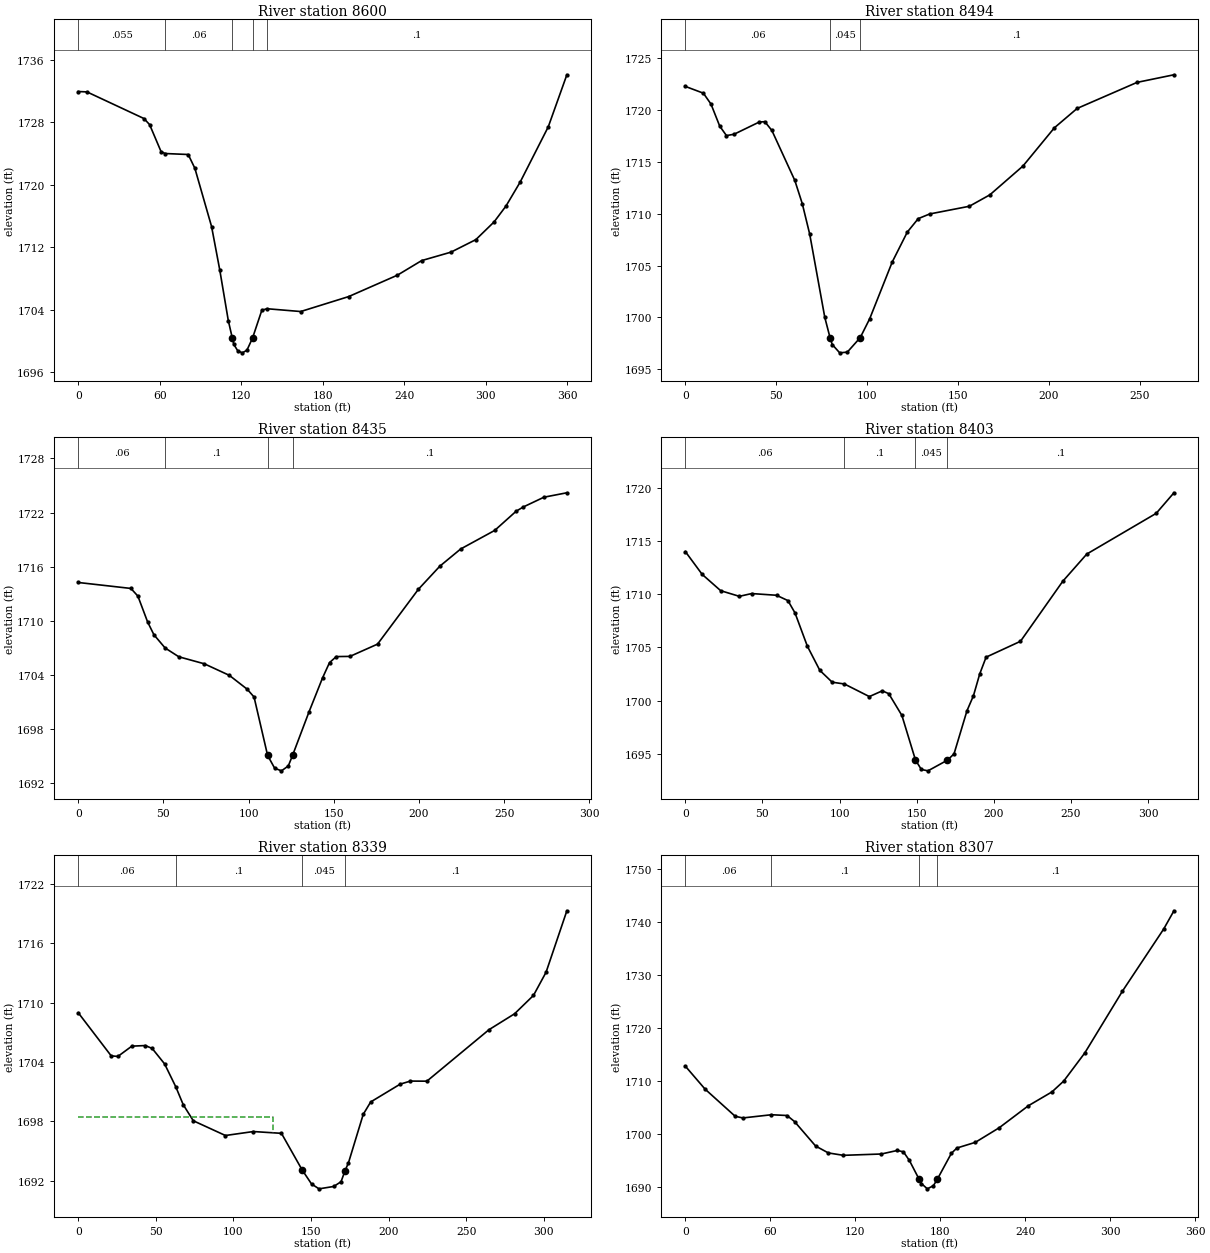
Type RM Length L Ch R = 1 ,8600    ,105.6,106.3,105.1
XS GIS Cut Line= 4
2445180.88416002632421.5702365692445111.50497948632400.006437211
2444968.99639242632366.2544034342444842.42626576632305.313231337
#Sta/Elev= 30
       0 1731.91     6.4 1731.86    48.3 1728.46    52.5 1727.68    60.9 1724.24
   63.851723.986    80.9 1723.86    85.8  1722.1    98.1 1714.65   104.1 1709.13
   110.4 1702.64  113.361700.395   114.5 1699.58   117.4 1698.76   120.7 1698.51
   124.1 1698.84  128.231700.391   135.1 1703.96   138.91704.148   163.7 1703.79
     199  1705.7   234.9 1708.44   252.7  1710.3   274.3 1711.38   292.6 1712.98
     306 1715.24   314.8 1717.28   325.2 1720.33   345.9  1727.4359.5812 1734.05
#Mann= 5 ,-1 , 0
       0    .055       0   63.85     .06       0  113.36    .045       0
  128.23     .06       0   138.9      .1       0
Bank Sta=113.36,128.23
XS Rating Curve= 0 ,0
Exp/Cntr(USF)=0,0
Exp/Cntr=0.5,0.3

Type RM Length L Ch R = 1 ,8494    ,60.1,58.8,58.2
XS GIS Cut Line= 4
2445192.13483795632317.501465757 2445153.6950217632304.375674843
2445013.06154763632268.7485280792444946.49503657632219.058033907
#Sta/Elev= 30
       0 1722.23     9.9 1721.58    14.1 1720.53    18.9 1718.41    22.6  1717.5
    26.8 1717.63    40.6  1718.8    43.7 1718.84    47.6 1717.99    60.2 1713.19
    64.3 1710.96    68.4 1708.02    76.7 1700.01   79.581698.064    80.8  1697.4
    84.9  1696.6    89.1 1696.67   96.191698.063   101.4 1699.88   113.8 1705.34
   122.1 1708.22   128.1 1709.51   134.4 1709.96   156.2  1710.7   167.5  1711.8
   185.7 1714.57     203 1718.25   215.5 1720.11   248.5 1722.62268.7628 1723.35
#Mann= 3 ,-1 , 0
       0     .06       0   79.58    .045       0   96.19      .1       0
#XS Ineff= 2 , 0
              541705.713     120        1705.713
Permanent Ineff=
       F       F
Bank Sta=79.58,96.19
XS Rating Curve= 0 ,0
Exp/Cntr(USF)=0,0
Exp/Cntr=0.5,0.3

Type RM Length L Ch R = 1 ,8435    ,36.9,32.1,25.9
XS GIS Cut Line= 4
 2445245.5755581632248.122285215 2445168.6959256632241.559389759
2445074.94027622632232.1838248212444961.49594047632210.620025463
#Sta/Elev= 30
       0 1714.26    30.9  1713.6      35 1712.75    40.7 1709.89    44.4 1708.47
   50.991707.002      59 1706.03      74 1705.25    88.7 1703.97    99.2 1702.43
   103.2 1701.57  111.161695.096   115.3 1693.68   119.3 1693.39   123.3 1693.93
   125.81695.099   135.4 1699.89   143.4 1703.68   147.5 1705.38   151.5 1706.05
   159.5 1706.07   175.7 1707.43   199.7 1713.51   212.3 1716.07   224.5 1717.97
   244.5 1720.03   257.1 1722.16   261.2 1722.62   273.4 1723.71286.8581  1724.2
#Mann= 4 ,-1 , 0
       0     .06       0   50.99      .1       0  111.16    .045       0
   125.8      .1       0
Bank Sta=111.16,125.8
XS Rating Curve= 0 ,0
Exp/Cntr(USF)=0,0
Exp/Cntr=0.5,0.3

Type RM Length L Ch R = 1 ,8403    ,68.1,63.5,61.3
XS GIS Cut Line= 4
2445289.56529497632204.3277768742445170.02872382632193.542522334
2445106.21596779632215.1130314142444979.48922695632189.048666275
#Sta/Elev= 30
       0 1713.99    10.9 1711.85    22.9 1710.32      35 1709.79      43 1710.05
    59.1 1709.89    66.5 1709.39    71.1 1708.23    79.1 1705.11    87.2 1702.84
    95.2 1701.73  103.111701.563   119.3 1700.38   127.7 1700.92   131.9 1700.65
   140.4 1698.61   149.2 1694.43     153 1693.54   157.3 1693.41   169.9 1694.41
   174.2    1695   182.6 1699.05   186.8 1700.46   190.9 1702.52     195 1704.08
   217.3 1705.57   244.7  1711.2   260.3 1713.76   305.3 1717.58   316.8 1719.51
#Mann= 4 ,-1 , 0
       0     .06       0  103.11      .1       0   149.2    .045       0
   169.9      .1       0
#XS Ineff= 2 , 0
             119 1698.42     200         1698.42
Permanent Ineff=
       F       F
Bank Sta=149.2,169.9
XS Rating Curve= 0 ,0
Exp/Cntr(USF)=0,0
Exp/Cntr=0.5,0.3

Type RM Length L Ch R = 1 ,8339    ,20.4,32.3,43
XS GIS Cut Line= 4
2445285.97021013632185.4535814292445165.53486776632129.729766305
2445097.22825568632173.7695556772444997.46465118 632159.38921629
#Sta/Elev= 30
       0 1708.98    21.2 1704.63    25.5 1704.57    34.5 1705.61    43.2 1705.67
    47.6 1705.38    55.6 1703.82   62.821701.502    67.6  1699.7    74.1 1698.07
    94.8 1696.58   112.8 1696.98   130.9  1696.8   144.2 1693.11   150.3 1691.68
   155.1 1691.19   164.6 1691.43   169.3 1691.91   171.8 1692.99   174.1 1693.83
   183.6 1698.72   188.4 1699.97   207.4 1701.77     214 1702.08   224.6 1702.07
   264.6 1707.27   281.1 1708.88   293.3 1710.74   301.4 1713.08   314.8 1719.29
#Mann= 4 ,-1 , 0
       0     .06       0   62.82      .1       0   144.2    .045       0
   171.8      .1       0
#XS Ineff= 2 , 0
           125.6 1698.46
Permanent Ineff=
       F       F
Bank Sta=144.2,171.8
XS Rating Curve= 0 ,0
Exp/Cntr(USF)=0,0
Exp/Cntr=0.5,0.3

Type RM Length L Ch R = 1 ,8307    ,141.3,150.2,154.1
XS GIS Cut Line= 4
2445311.20451266632181.5557741552445215.57375029632134.677949465
2445116.19276195632099.988359194 2444987.7475223 632064.36121243
#Sta/Elev= 30
       0 1712.81    13.9 1708.49    35.2 1703.36    40.6 1703.05   60.831703.654
    71.8 1703.51    77.1 1702.37      92 1697.75     101 1696.45   111.6    1696
   138.4 1696.25   149.7 1696.92     154 1696.66   158.2 1695.04  164.981691.545
   166.7 1690.68   170.9 1689.68   175.2 1690.28  178.051691.543   187.9 1696.39
   191.8 1697.38   204.8 1698.45   221.6 1701.19   242.3 1705.36   258.9 1707.96
   267.2    1710   282.1 1715.31   308.7 1726.97   337.8 1738.67345.0585 1742.12
#Mann= 4 ,-1 , 0
       0     .06       0   60.83      .1       0  164.98    .045       0
  178.05      .1       0
Bank Sta=164.98,178.05
XS Rating Curve= 0 ,0
Exp/Cntr(USF)=0,0
Exp/Cntr=0.5,0.3

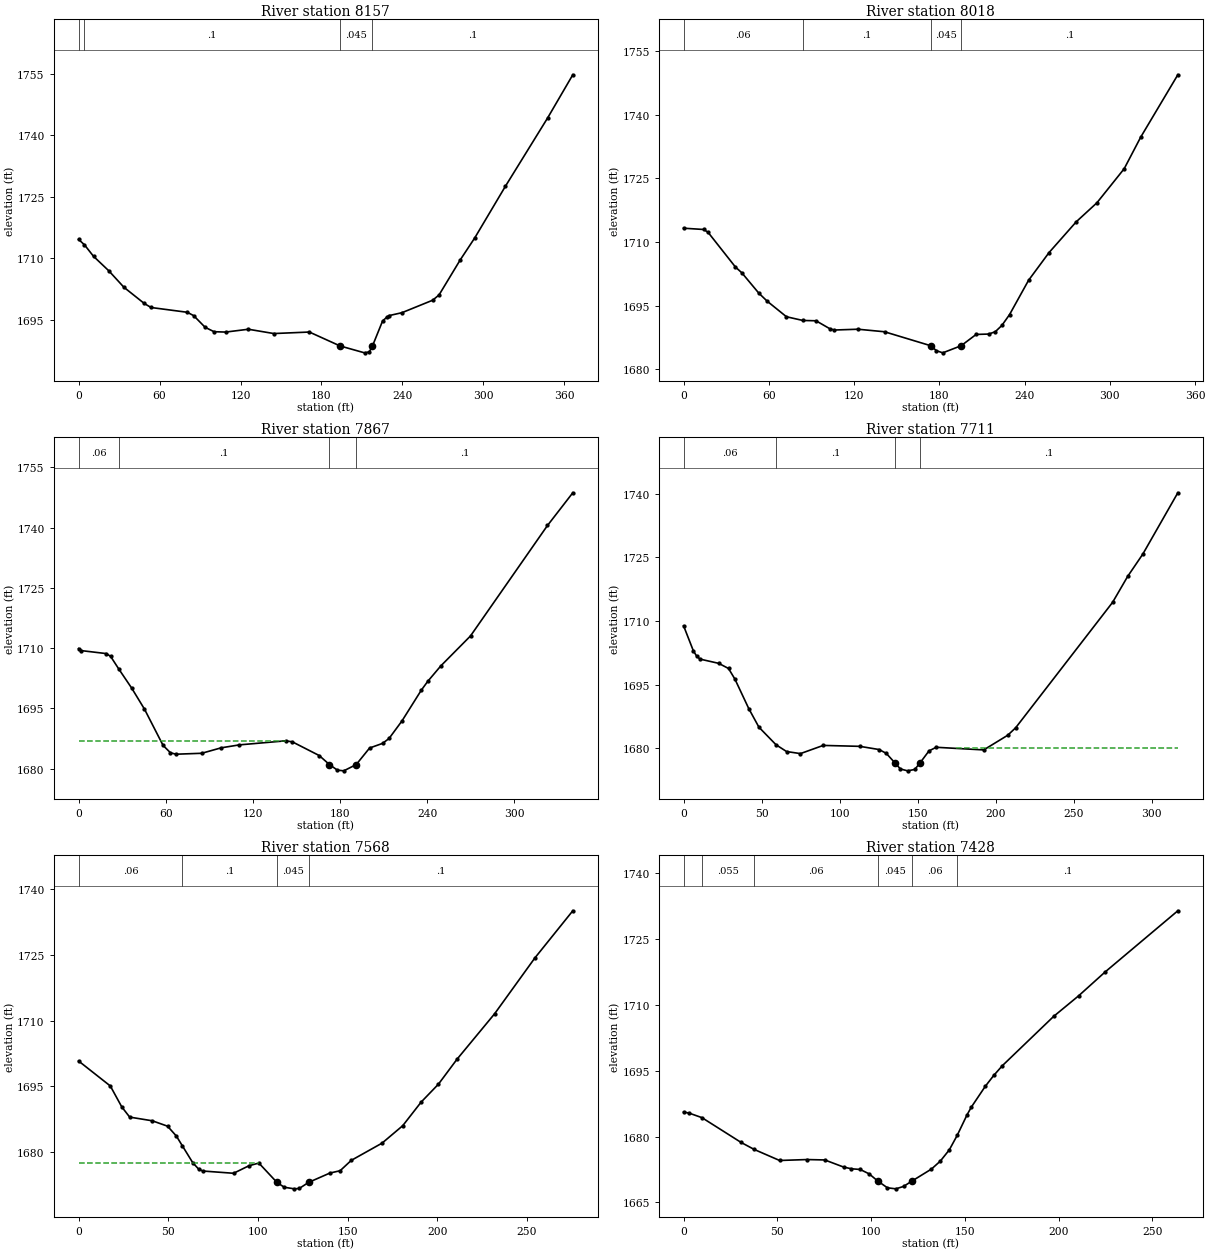
Type RM Length L Ch R = 1 ,8157    ,133.9,138.9,137.7
XS GIS Cut Line= 4
 2445381.5212497632135.6155059592445284.01537434632061.548542948
2445209.01085484631960.2924416182445119.00543143 631884.35036562
#Sta/Elev= 30
       0 1714.56    4.391713.225    11.1 1710.42    22.5 1706.86    33.6 1702.87
    48.7 1698.91    53.7 1697.93    80.6 1696.76    85.3 1695.94    93.8 1693.09
   100.4 1692.02     109 1691.93   125.8 1692.62   144.7 1691.57     171 1691.94
  193.79 1688.54   211.9 1686.86   215.4 1687.08  217.791688.539   225.3 1694.66
   228.2  1695.5   230.3 1695.97   239.6 1696.66   262.4 1699.71   267.1 1700.99
   282.8 1709.55   293.6 1714.94   316.3 1727.54   347.6 1744.23366.2202 1754.75
#Mann= 4 ,-1 , 0
       0     .06       0    4.39      .1       0  193.79    .045       0
  217.79      .1       0
Bank Sta=193.79,217.79
XS Rating Curve= 0 ,0
Exp/Cntr(USF)=0,0
Exp/Cntr=0.3,0.1

Type RM Length L Ch R = 1 ,8018    ,150.4,151.1,151.7
XS GIS Cut Line= 4
2445445.27509128632107.4888111452445407.77283152632033.421848134
2445333.70586851631903.1014954962445269.95202693631807.470733128
#Sta/Elev= 30
       0 1713.24    14.1 1712.94    17.2 1712.28    36.5 1704.08      41 1702.72
    52.9 1697.94    58.9 1696.01    72.4 1692.36    83.91691.487    93.2 1691.41
   103.2 1689.48   106.2 1689.23   122.7 1689.42   141.4 1688.82     1741685.522
   177.9 1684.37   182.4 1683.85  195.311685.521   205.9 1688.19   214.8 1688.28
   219.4 1688.84     224 1690.31   229.4 1692.86   242.8 1700.96   257.2 1707.49
   276.4 1714.77   290.9 1719.23   310.1 1727.27   321.7  1734.7347.8516 1749.42
#Mann= 4 ,-1 , 0
       0     .06       0    83.9      .1       0     174    .045       0
  195.31      .1       0
Bank Sta=174,195.31
XS Rating Curve= 0 ,0
Exp/Cntr(USF)=0,0
Exp/Cntr=0.3,0.1

Type RM Length L Ch R = 1 ,7867    ,155.9,155.7,155
XS GIS Cut Line= 4
2445571.84521794632032.4842916412445549.34386209631998.732257864
2445458.40088219631811.2209591032445401.20993607631739.966665574
#Sta/Elev= 30
       0 1709.89       2 1709.37    19.2 1708.63    22.1 1707.92   27.641704.826
    36.6 1700.03    45.4  1694.8    58.2 1685.78    63.3 1683.94    67.1 1683.59
    84.8 1683.82    98.2 1685.18   110.7 1685.91   142.6 1686.92   147.2 1686.67
   165.7 1683.26  172.791681.008   178.2 1679.63   182.6 1679.45  191.191681.008
   200.4 1685.13   209.3 1686.28   213.8  1687.5   222.7 1691.87     236 1699.52
   240.4  1701.7   249.4 1705.55   269.9 1713.03   322.9 1740.52340.3335 1748.66
#Mann= 4 ,-1 , 0
       0     .06       0   27.64      .1       0  172.79    .045       0
  191.19      .1       0
#XS Ineff= 2 , 0
          143.01 1686.99
Permanent Ineff=
       F       F
Bank Sta=172.79,191.19
XS Rating Curve= 0 ,0
Exp/Cntr(USF)=0,0
Exp/Cntr=0.3,0.1

Type RM Length L Ch R = 1 ,7711    ,145.2,142.9,139.8
XS GIS Cut Line= 4
2445709.66602253631939.666198754 2445684.3519972631910.601947446
2445595.28413028  631751.21734352445540.90585364 631672.46259802
#Sta/Elev= 30
       0 1708.83     6.3  1702.9     8.3 1701.74    10.5 1700.99    22.5 1699.99
    28.8 1698.78    32.9 1696.27    41.8 1689.31    48.3 1684.94   59.281680.796
      66 1679.21    74.9 1678.72    89.5 1680.65     113 1680.43   125.3 1679.68
   129.9 1678.79  135.571676.497     139  1675.1   143.6 1674.66   148.2 1674.99
  151.491676.494   157.3 1679.35   161.9 1680.21   192.4 1679.59   207.8 1683.05
   212.9 1684.82     275 1714.36   284.7 1720.49   294.4 1725.74316.8298 1740.18
#Mann= 4 ,-1 , 0
       0     .06       0   59.28      .1       0  135.57    .045       0
  151.49      .1       0
#XS Ineff= 2 , 0
           93.15 1680.53  174.53         1680.08
Permanent Ineff=
       F       F
Bank Sta=135.57,151.49
XS Rating Curve= 0 ,0
Exp/Cntr(USF)=0,0
Exp/Cntr=0.3,0.1

Type RM Length L Ch R = 1 ,7568    ,141.6,139.7,137.6
XS GIS Cut Line= 4
2445827.79814075631815.9087415722445794.98366346 631785.90693377
2445688.10222317631681.8381629582445625.28593809631629.334999305
#Sta/Elev= 30
       0 1700.77    17.7 1695.07    24.1 1690.29    28.5 1687.97    41.1 1687.13
    49.6  1685.9    54.5 1683.66    57.91681.394    63.7 1677.54    67.1 1676.04
    69.4 1675.67    86.4 1675.16      95 1676.88   100.5 1677.49  110.611673.069
   114.7 1671.97   120.3 1671.61     123 1671.69  128.191673.072   140.1 1675.21
   145.8 1675.74     152  1678.1   169.2 1682.04   180.7 1686.01     191 1691.41
   200.6 1695.48     211 1701.19   231.9 1711.53   254.4 1724.29275.5085 1735.03
#Mann= 4 ,-1 , 0
       0     .06       0    57.9      .1       0  110.61    .045       0
  128.19      .1       0
#XS Ineff= 2 , 0
           100.4  1677.5
Permanent Ineff=
       F       F
Bank Sta=110.61,128.19
XS Rating Curve= 0 ,0
Exp/Cntr(USF)=0,0
Exp/Cntr=0.3,0.1

Type RM Length L Ch R = 1 ,7428    ,148.3,151.2,153.4
XS GIS Cut Line= 4
2445915.92845116 631684.650832442445869.05062647631649.961242169
2445776.23253359631590.8951830592445692.79000564631544.954914863
#Sta/Elev= 30
       0 1685.61       3 1685.35    9.771684.327    30.7 1678.67   37.661677.082
    51.2 1674.57    65.8 1674.78    75.3 1674.69    85.4 1673.06    89.5 1672.68
    94.2 1672.52      99 1671.51  103.491669.909   108.7 1668.35   113.2 1668.11
   117.3 1668.66   121.9 1669.91   132.2 1672.62   136.9 1674.42   141.7 1676.98
   145.91680.271   151.1  1684.9   153.4 1686.69   160.9 1691.46   165.4 1693.93
     170 1696.16   197.4  1707.4   210.7 1712.08   224.8  1717.5263.5885 1731.44
#Mann= 6 ,-1 , 0
       0      .1       0    9.77    .055       0   37.66     .06       0
  103.49    .045       0   121.9     .06       0   145.9      .1       0
Bank Sta=103.49,121.9
XS Rating Curve= 0 ,0
Exp/Cntr(USF)=0,0
Exp/Cntr=0.3,0.1

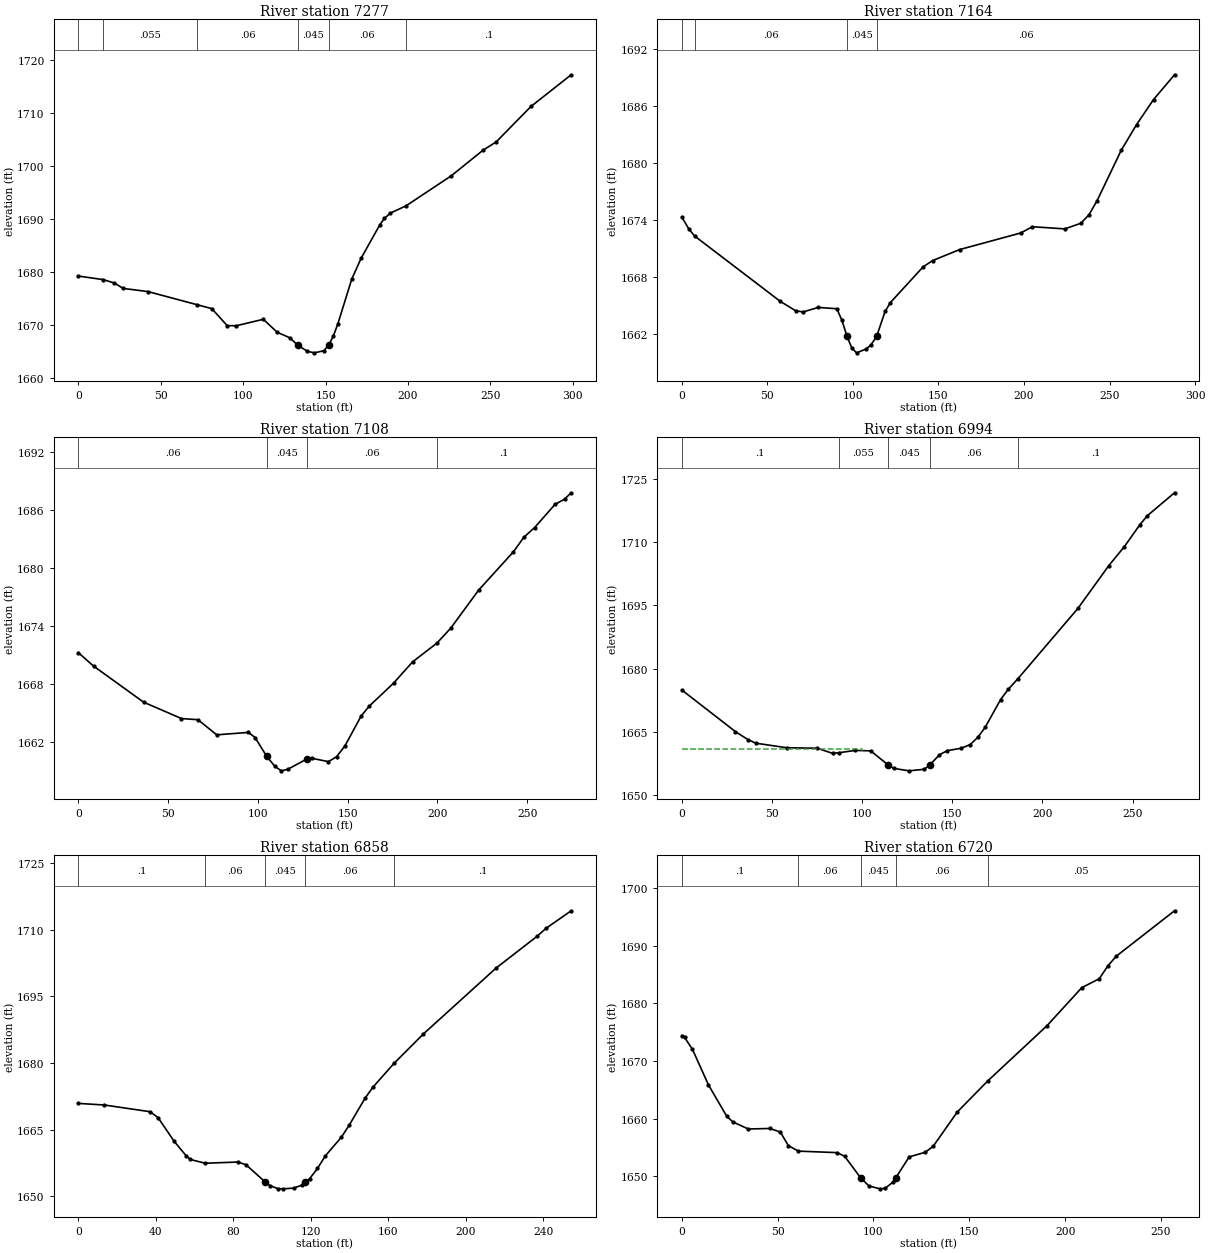
Type RM Length L Ch R = 1 ,7277    ,113.6,113.8,112.9
XS GIS Cut Line= 4
2446004.99631808631606.833643454 2445956.2433804631550.580253826
2445867.17551349 631453.07437847  2445790.295881631401.508771311
#Sta/Elev= 30
       0 1679.27   14.991678.604    21.8 1677.96    27.1 1676.95    42.3 1676.34
   72.111673.865    80.9 1673.14    90.3 1669.93    95.7 1669.91   112.2 1671.13
   120.6 1668.69   128.2 1667.66  133.141666.238     139 1665.09   143.2 1664.81
   148.9  1665.2  151.851666.241   154.6  1667.9   157.4 1670.23   165.9 1678.72
   171.5 1682.59   182.9 1688.92   185.7 1690.13   189.3 1691.13  198.761692.488
   226.3 1698.16   245.6 1702.99   253.5 1704.53   274.7 1711.23299.0738 1717.19
#Mann= 6 ,-1 , 0
       0      .1       0   14.99    .055       0   72.11     .06       0
  133.14    .045       0  151.85     .06       0  198.76      .1       0
Bank Sta=133.14,151.85
XS Rating Curve= 0 ,0
Exp/Cntr(USF)=0,0
Exp/Cntr=0.5,0.3

Type RM Length L Ch R = 1 ,7164    ,52.7,55.9,59.5
XS GIS Cut Line= 4
2446064.06237719631543.0798018752446029.37278691631469.012838865
2445974.99451027631416.5096752122445864.36284401 631347.13049467
#Sta/Elev= 30
       0 1674.29     4.1 1673.03    7.461672.291    57.6 1665.39    66.5 1664.41
    70.9 1664.28    79.7 1664.76    90.6 1664.62    93.6 1663.39   96.561661.703
    99.3  1660.5   102.1 1659.97   107.8 1660.38   110.6 1660.82  113.861661.699
   118.8 1664.33   121.9 1665.27     141 1669.03   146.6  1669.7   162.4 1670.86
   198.1 1672.61   204.9 1673.27   223.8 1673.04   233.2 1673.63   237.9 1674.51
   242.7 1676.01   256.8 1681.32   265.8 1684.04   275.7 1686.68287.9628 1689.29
#Mann= 4 ,-1 , 0
       0      .1       0    7.46     .06       0   96.56    .045       0
  113.86     .06       0
#XS Ineff= 2 , 0
              80 1663.62     130         1663.62
Permanent Ineff=
       F       F
Bank Sta=96.56,113.86
XS Rating Curve= 0 ,0
Exp/Cntr(USF)=0,0
Exp/Cntr=0.5,0.3

Type RM Length L Ch R = 1 ,7108    ,111.3,113.3,115.3
XS GIS Cut Line= 4
2446118.44065383631517.7657765432446084.68862005631469.950395359
2446027.49767393631364.0065115592445982.49496222631279.626427117
#Sta/Elev= 30
       0 1671.21     8.4 1669.84    36.3 1666.11    57.4 1664.42    66.6  1664.3
      77 1662.74    94.7 1662.99    98.4 1662.46   104.91660.511   109.5 1659.47
   113.1 1659.02   116.6 1659.18   127.2 1660.24   130.2 1660.31   139.3 1659.97
   143.8 1660.48   148.4 1661.57   157.5 1664.68     162  1665.7   175.6 1668.08
   186.2 1670.28  199.751672.215   207.4 1673.75     223 1677.69   242.4 1681.65
   248.2 1683.15   254.2 1684.15   265.5 1686.53   270.9 1687.09274.5534 1687.74
#Mann= 4 ,-1 , 0
       0     .06       0   104.9    .045       0   127.2     .06       0
  199.75      .1       0
Bank Sta=104.9,127.2
XS Rating Curve= 0 ,0
Exp/Cntr(USF)=0,0
Exp/Cntr=0.5,0.3

Type RM Length L Ch R = 1 ,6994    ,134.9,136.7,137.9
XS GIS Cut Line= 4
2446207.50852074631500.8897596542446186.88227787631450.261708989
2446147.50490513631336.8173732392446111.87775837631244.936836846
#Sta/Elev= 30
       0 1674.97    29.7 1665.13    36.7 1663.22      41 1662.38    58.2  1661.3
    75.2 1661.18    83.6 1659.97   87.021660.112    96.3 1660.67   104.8 1660.56
   114.41657.235   117.5 1656.42     126 1655.83   134.5  1656.2  137.571657.235
   142.9 1659.63   147.2  1660.6   154.9 1661.18   159.9 1662.02   164.3 1663.82
   168.3 1666.15   176.8 1672.69   181.1 1675.14  186.241677.549   219.7 1694.28
   236.9 1704.45   245.5 1708.93   254.1 1714.11   258.3 1716.27273.2986 1721.67
#Mann= 5 ,-1 , 0
       0      .1       0   87.02    .055       0   114.4    .045       0
  137.57     .06       0  186.24      .1       0
#XS Ineff= 2 , 0
             100 1660.98
Permanent Ineff=
       F       F
Bank Sta=114.4,137.57
XS Rating Curve= 0 ,0
Exp/Cntr(USF)=0,0
Exp/Cntr=0.3,0.1

Type RM Length L Ch R = 1 ,6858    ,138.2,137.2,136.5
XS GIS Cut Line= 4
2446323.76552597631462.4499434082446307.82706557 631406.19655378
2446284.38815323631303.0653394622446252.51123244631218.685255019
#Sta/Elev= 30
       0 1670.89    13.4 1670.53      37 1669.02    41.1 1667.68    49.4 1662.36
    55.5 1659.15    57.7 1658.28   65.341657.426    82.4 1657.69    86.5 1657.08
   96.481653.185    98.8 1652.41   102.9 1651.71   105.6 1651.66   111.1 1651.82
   115.2 1652.46  117.221653.187   119.3 1653.92   123.4 1656.24   127.5 1659.09
   135.7 1663.25   139.8 1665.99     148 1672.06   152.1 1674.57  163.111679.978
   178.1 1686.52   215.7 1701.37   236.8  1708.5   241.4 1710.29254.4295 1714.25
#Mann= 5 ,-1 , 0
       0      .1       0   65.34     .06       0   96.48    .045       0
  117.22     .06       0  163.11      .1       0
Bank Sta=96.48,117.22
XS Rating Curve= 0 ,0
Exp/Cntr(USF)=0,0
Exp/Cntr=0.3,0.1

Type RM Length L Ch R = 1 ,6720    ,156.1,155,153.8
XS GIS Cut Line= 4
2446462.52388705631436.1983615822446448.46053965631388.382980398
2446416.58361886631288.0644355612446374.39357663631195.246342674
#Sta/Elev= 30
       0 1674.39     1.4 1674.11     5.5 1672.06    13.9 1665.86    23.4 1660.44
    26.6 1659.44    34.7 1658.21      46  1658.3    51.4 1657.68    55.6 1655.32
   60.811654.371    81.1 1654.11      85 1653.46   93.251649.763    97.6 1648.34
   103.4 1647.83     106 1647.89   110.2 1649.01   111.71649.764   118.6 1653.37
     127 1654.17   131.2 1655.23   143.7 1661.15  159.621666.546   190.6 1676.15
   208.7 1682.73   217.8 1684.27   222.3 1686.51   226.7 1688.19257.0588 1696.06
#Mann= 5 ,-1 , 0
       0      .1       0   60.81     .06       0   93.25    .045       0
   111.7     .06       0  159.62     .05       0
Bank Sta=93.25,111.7
XS Rating Curve= 0 ,0
Exp/Cntr(USF)=0,0
Exp/Cntr=0.3,0.1