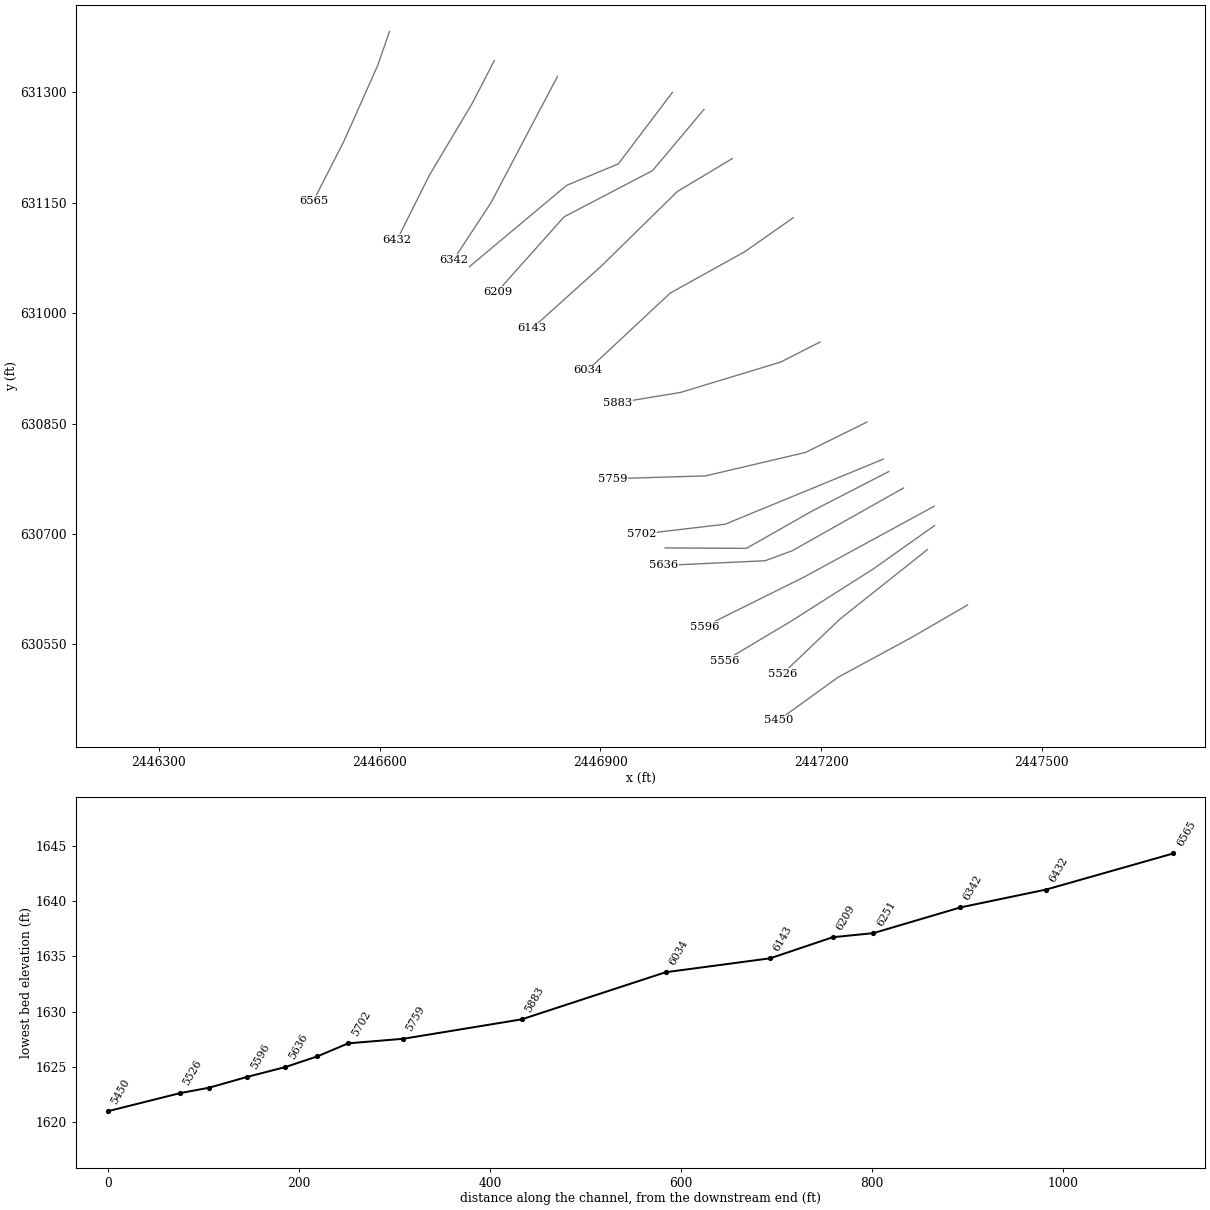
HEC-RAS study HAMMERRN.prj: HAMMERRN

--- HAMMERRN.g01 (geometry) --- (continued)

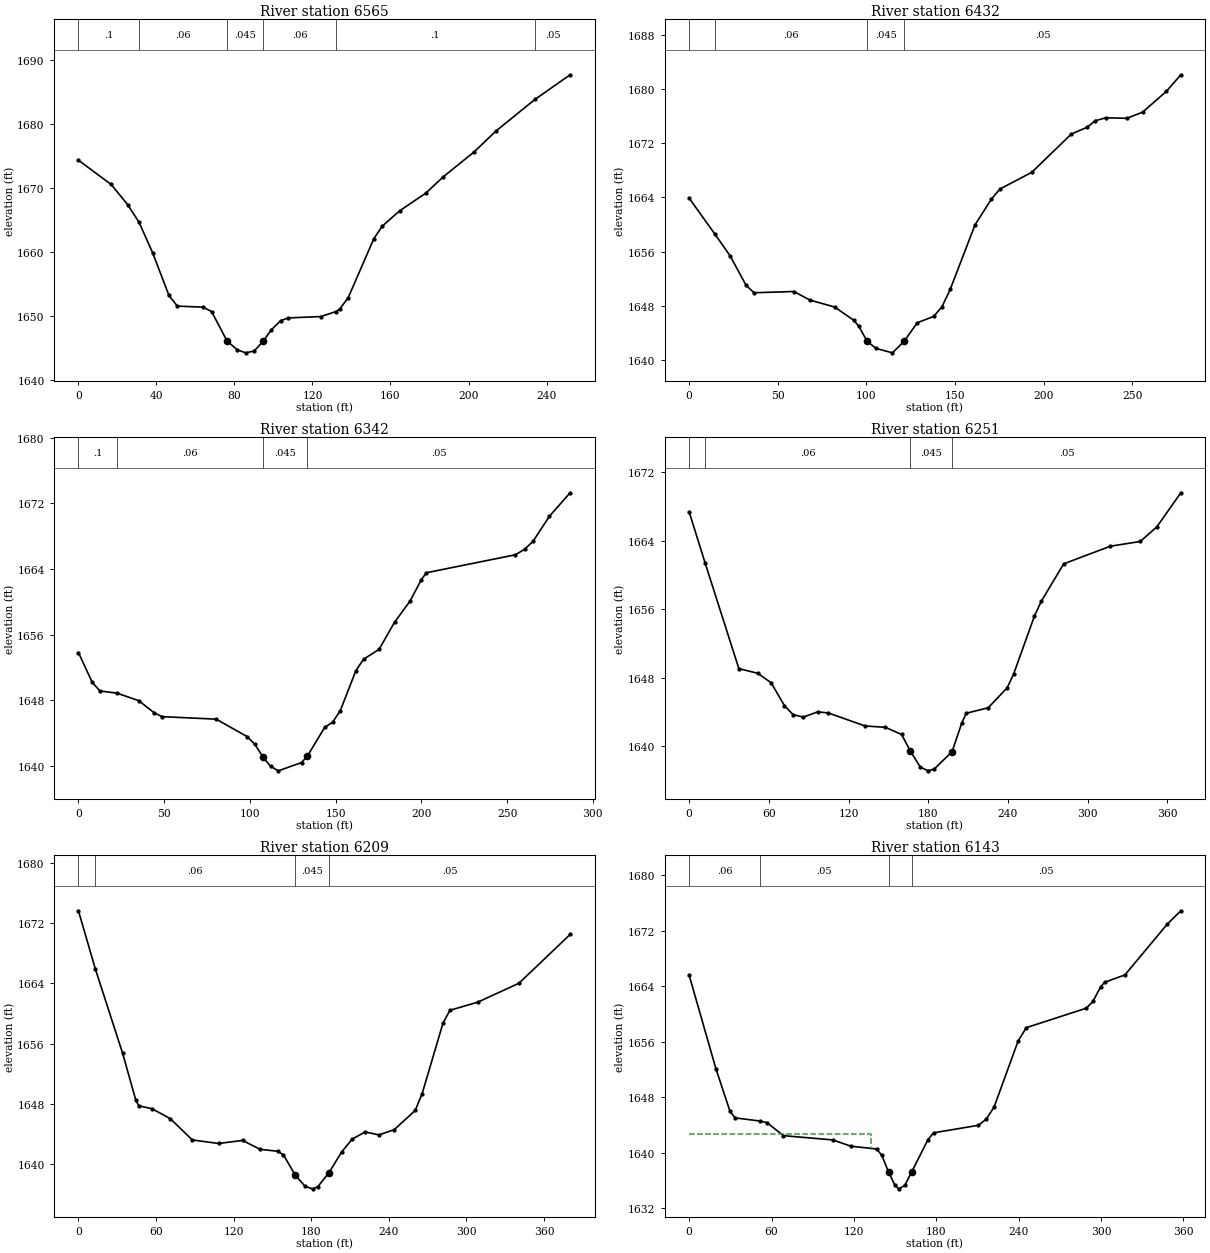
Type RM Length L Ch R = 1 ,6565    ,134.6,133.1,131.9
XS GIS Cut Line= 4
2446613.47048255631382.7576414352446597.53202216631336.817373239
2446551.59175396 631233.686158922446510.33926824631153.056300453
#Sta/Elev= 30
       0 1674.41    16.8 1670.62    25.3 1667.45   31.111664.689      38 1659.99
    46.4 1653.29    50.7 1651.62    63.9 1651.46    68.3 1650.76   76.151646.183
    81.4  1644.8    85.8 1644.32    90.1  1644.6   94.841646.185    98.9 1647.91
   103.7 1649.36   107.7 1649.78   124.3 1649.99  131.83 1650.75   133.9 1651.14
   138.3 1652.93   151.5 1662.18   155.8 1664.12   164.7 1666.51   178.1 1669.27
   187.1 1671.83   202.8 1675.69   214.1 1678.98  234.051683.907252.0973 1687.76
#Mann= 6 ,-1 , 0
       0      .1       0   31.11     .06       0   76.15    .045       0
   94.84     .06       0  131.83      .1       0  234.05     .05       0
Bank Sta=76.15,94.84
XS Rating Curve= 0 ,0
Exp/Cntr(USF)=0,0
Exp/Cntr=0.3,0.1

Type RM Length L Ch R = 1 ,6432    ,88.5,90.1,89.1
XS GIS Cut Line= 4
2446755.97906961631343.3802686952446725.97726181631285.251766079
2446667.84875919631187.7458907242446623.78360399631099.615580306
#Sta/Elev= 30
       0 1663.91   14.31 1658.67    23.1 1655.39    32.1 1651.04    36.6 1649.93
    59.1 1650.11    68.2 1648.84    82.1 1647.82    92.8 1645.88    95.8 1644.96
  100.34 1642.79   105.4 1641.71   114.7 1641.05  121.45 1642.79   128.7 1645.49
     138 1646.43   142.7 1647.87   147.3 1650.41   161.3 1659.95   170.6 1663.77
   175.3 1665.24   193.3 1667.71   215.7 1673.38   224.6 1674.38   229.1 1675.33
   235.1 1675.78     247  1675.7   255.9 1676.61   269.3 1679.68277.4649 1682.13
#Mann= 4 ,-1 , 0
       0      .1       0   14.31     .06       0  100.34    .045       0
  121.45     .05       0
Bank Sta=100.34,121.45
XS Rating Curve= 0 ,0
Exp/Cntr(USF)=0,0
Exp/Cntr=0.3,0.1

Type RM Length L Ch R = 1 ,6342    ,101.4,90.9,79.8
XS GIS Cut Line= 3
2446841.92087265631321.998808446 2446751.4583951631150.221557571
 2446700.6211029631072.836592132
#Sta/Elev= 30
       01653.828   8.0331650.201  12.5541649.146   22.421648.889  35.1581647.966
    44.21646.489   48.721646.024  80.3661645.714  98.4491643.583  102.971642.631
  107.491641.142 112.0111639.984 116.5321639.424 130.0941640.431  133.541641.229
 143.6571644.733 148.1771645.333 152.6981646.746  161.741651.598  166.261653.015
 175.3021654.209 184.343 1657.52 193.3851660.088  199.951662.695 202.9121663.542
  254.831665.728 260.344 1666.42  265.13 1667.38 274.701 1670.43 286.7311673.278
#Mann= 4 ,-1 , 0
       0      .1       0   22.42     .06       0  107.49    .045       0
  133.54     .05       0
Bank Sta=107.49,133.54
XS Rating Curve= 0 ,0
Exp/Cntr(USF)=0,0
Exp/Cntr=0.5,0.3

Type RM Length L Ch R = 1 ,6251    ,40.2,42.5,45.2
XS GIS Cut Line= 4
 2446997.9506174631300.1214636222446924.57154112631203.014828316
2446854.20755001631173.7541981042446722.13000648631063.287253754
#Sta/Elev= 30
       01667.358  11.9521661.424  37.4351649.039  51.7141648.498  61.7061647.391
  71.7331644.716    78.31643.663  85.9821643.374  96.8011643.998 104.8391643.856
 132.3851642.345 147.6831642.185 159.9221641.349   166.61639.383 174.1241637.518
 180.0091637.099 184.5411637.327   197.9 1639.33 205.2491642.702 208.6171643.831
 225.127 1644.47 239.3251646.794  244.151648.371 259.7941655.137 265.0091656.901
  281.921661.288 317.1551663.351 339.5471663.901 352.0171665.604 370.1031669.592
#Mann= 4 ,-1 , 0
       0      .1       0  11.952     .06       0   166.6    .045       0
   197.9     .05       0
#XS Ineff= 2 , 0
             146 1642.19     217         1642.19
Permanent Ineff=
       F       F
Bank Sta=166.6,197.9
XS Rating Curve= 0 ,0
Exp/Cntr(USF)=0,0
Exp/Cntr=0.5,0.3

Type RM Length L Ch R = 1 ,6209    ,60.8,65.5,70.5
XS GIS Cut Line= 4
2447040.80876727631276.9273376042446971.07482656631193.868522286
2446850.73035153631130.9882918012446760.17576019631029.524554853
#Sta/Elev= 30
       01673.631  13.1051665.888  34.141 1654.73  44.4421648.457  46.7551647.747
  56.8541647.363   71.051646.043  88.0851643.214 108.4511642.749 126.8751643.153
 140.5451641.969 153.9541641.719 158.467 1641.26 167.4931638.596 175.343 1637.05
 181.0331636.729 185.0091636.993   193.81638.889 203.5981641.635 211.687 1643.32
 221.6511644.278 232.4371643.886 244.2331644.587 260.4471647.132 265.8091649.377
 281.8931658.705 287.2541660.427   308.71661.496 340.6131664.008 380.2291670.488
#Mann= 4 ,-1 , 0
       0      .1       0  13.105     .06       0 167.493    .045       0
   193.8     .05       0
Bank Sta=167.493,193.8
XS Rating Curve= 0 ,0
Exp/Cntr(USF)=0,0
Exp/Cntr=0.5,0.3

Type RM Length L Ch R = 1 ,6143    ,110.3,109.4,101.1
XS GIS Cut Line= 4
2447079.43605997631210.2472465752447004.43154047631165.244534873
2446901.30032615631063.9884335422446807.54467677  630979.6083491
#Sta/Elev= 30
       0 1665.59    19.5 1652.12    29.8 1645.96    33.5 1645.04   51.651644.585
    56.8 1644.34    68.7 1642.48   104.5 1641.87   117.9 1640.96   136.5 1640.56
   140.3 1639.67  145.221637.245   149.7  1635.4   152.6 1634.82   157.1 1635.31
  162.041637.246   173.9 1641.88     178 1642.89   210.7 1643.97   216.4 1644.86
   222.1 1646.59   239.6  1656.1   245.6 1658.04   289.3 1660.84   294.1 1661.82
   299.7 1663.91   302.6 1664.57   317.4 1665.63   348.4 1672.98358.1346 1674.87
#Mann= 4 ,-1 , 0
       0     .06       0   51.65     .05       0  145.22    .045       0
  162.04     .05       0
#XS Ineff= 2 , 0
          132.26 1642.69
Permanent Ineff=
       F       F
Bank Sta=145.22,162.04
XS Rating Curve= 0 ,0
Exp/Cntr(USF)=0,0
Exp/Cntr=0.3,0.1

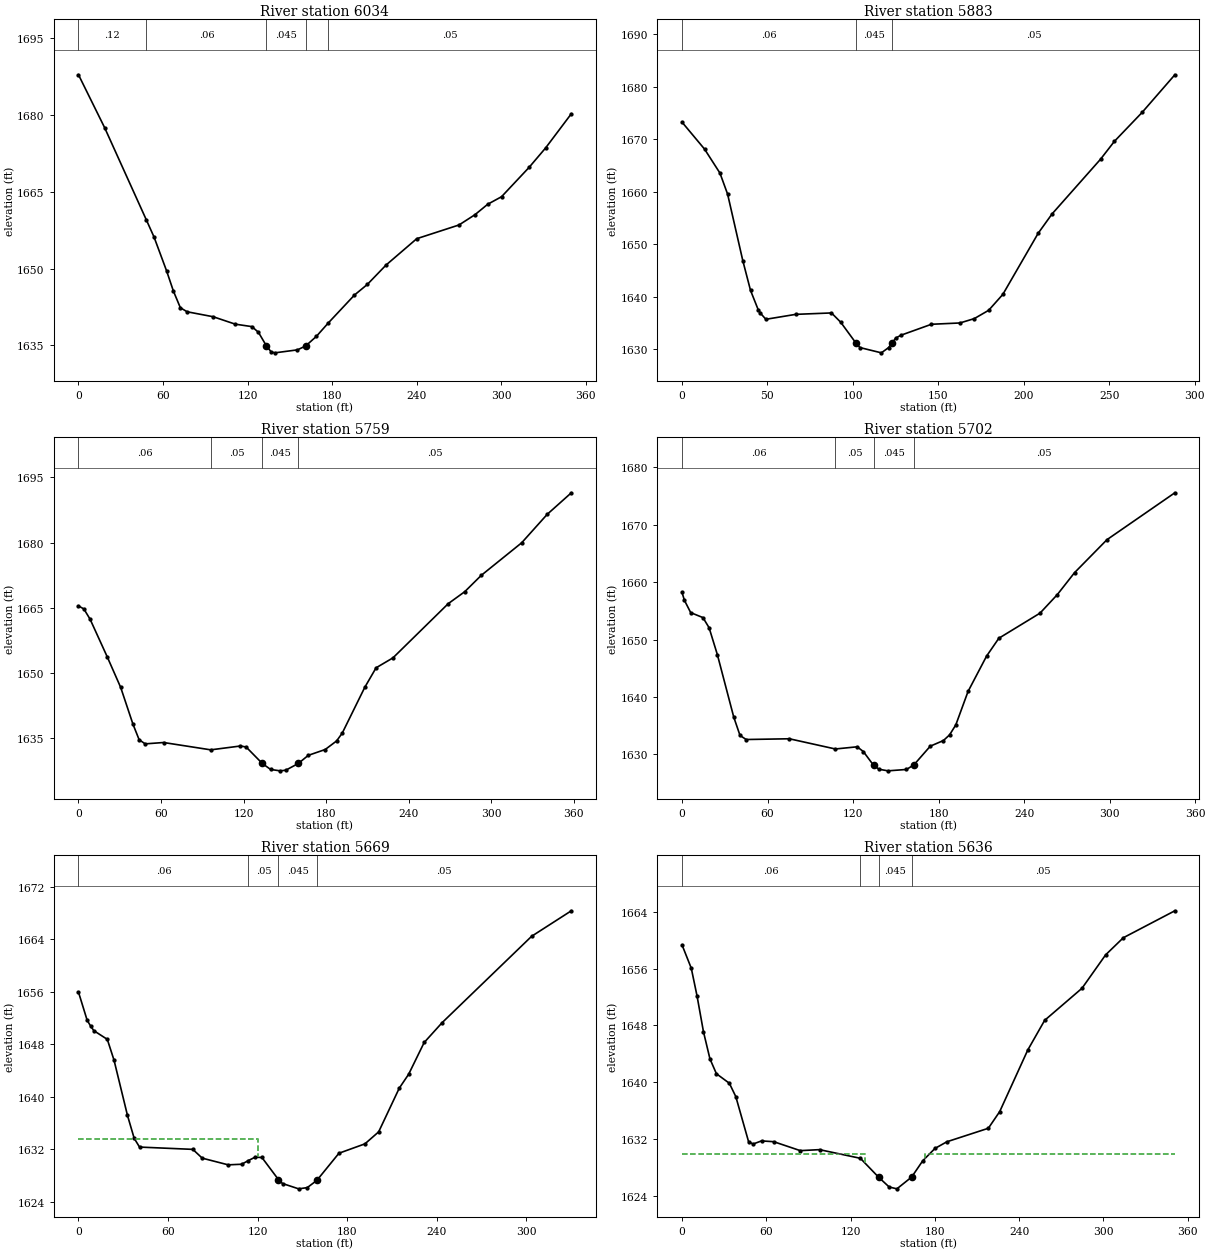
Type RM Length L Ch R = 1 ,6034    ,151.3,150.8,145.6
XS GIS Cut Line= 4
2447161.94103143631129.6173881082447096.31207686631083.677119912
2446995.05597553631027.4237302842446882.54919628630922.417402978
#Sta/Elev= 30
       0 1687.86    18.5 1677.56   48.111659.551    53.6 1656.19    62.5 1649.59
    67.4  1645.6    72.3 1642.37    77.1 1641.58    95.6 1640.61   111.3 1639.16
   123.1 1638.68   127.7 1637.58  133.441634.902   136.8 1633.73   139.4 1633.56
   155.4 1634.14  161.261634.904   168.8 1636.76  177.391639.415   195.9 1644.85
     205 1646.91   218.3  1650.7   240.1 1655.85   270.1 1658.53   281.4 1660.53
   290.5 1662.58   300.3 1664.05   319.8 1669.76   331.6 1673.58349.8396 1680.25
#Mann= 5 ,-1 , 0
       0     .12       0   48.11     .06       0  133.44    .045       0
  161.26     .06       0  177.39     .05       0
Bank Sta=133.44,161.26
XS Rating Curve= 0 ,0
Exp/Cntr(USF)=0,0
Exp/Cntr=0.3,0.1

Type RM Length L Ch R = 1 ,5883    ,124.8,124.1,123.4
XS GIS Cut Line= 4
2447198.50573469630960.8572192242447145.06501454630933.668080903
2447009.11932294630892.415595176  2446923.801682630878.352247769
#Sta/Elev= 30
       0 1673.23    13.2 1668.09    22.2 1663.53    26.7 1659.51    35.6 1646.83
    40.1 1641.19    44.6  1637.5    45.9 1636.84    49.1 1635.68    66.6 1636.62
    87.5 1636.89    92.9 1635.12  101.711631.199   104.2 1630.29   116.7 1629.29
   120.9 1630.28  123.021631.199   125.1  1632.1   128.2 1632.65     146 1634.73
   162.7 1634.98   171.1 1635.81   179.5 1637.39   187.8 1640.42   208.5 1652.07
   216.6 1655.74     245 1666.17   253.1 1669.57   269.3 1675.07288.4955 1682.25
#Mann= 3 ,-1 , 0
       0     .06       0  101.71    .045       0  123.02     .05       0
Bank Sta=101.71,123.02
XS Rating Curve= 0 ,0
Exp/Cntr(USF)=0,0
Exp/Cntr=0.3,0.1

Type RM Length L Ch R = 1 ,5759    ,55.4,57.4,59.7
XS GIS Cut Line= 4
2447262.25957627630852.1006659422447178.81704832630810.848180215
2447042.87135672630778.9712594262446917.23878655 630775.22103345
#Sta/Elev= 30
       0 1665.43     3.9 1664.74     8.4  1662.4    20.8  1653.8    30.7 1646.69
    39.6 1638.26    44.1 1634.68    48.5 1633.73    61.9 1634.04   96.171632.356
   117.8 1633.24   121.9 1633.01  133.671629.222   139.7 1627.85   146.6 1627.53
   150.7 1627.67  159.851629.222   167.1 1631.09   179.4 1632.43   187.7  1634.4
   191.8  1636.2   208.2 1646.73   216.4 1651.21   228.7  1653.5   268.9 1665.96
   280.9 1668.71   292.9 1672.46   322.3 1679.95   340.9  1686.5358.4044 1691.44
#Mann= 4 ,-1 , 0
       0     .06       0   96.17     .05       0  133.67    .045       0
  159.85     .05       0
Bank Sta=133.67,159.85
XS Rating Curve= 0 ,0
Exp/Cntr(USF)=0,0
Exp/Cntr=0.3,0.1

Type RM Length L Ch R = 1 ,5702    ,30.5,32.2,34.1
XS GIS Cut Line= 3
2447284.35398458630801.6840387072447069.62547662630713.322772915
2446956.81483655630700.044953771
#Sta/Elev= 30
       0 1658.23     1.7 1656.84     6.1  1654.7    14.7 1653.83      19 1652.07
    24.8 1647.38    36.3 1636.49    40.7 1633.29      45 1632.58    75.3 1632.71
   107.6 1630.93   122.9 1631.31   127.2 1630.49   134.4 1628.09   138.2  1627.4
   144.5 1627.12   157.5 1627.36   162.7 1628.16   174.2 1631.42   183.4  1632.4
   187.7 1633.38   192.1 1635.12   200.7 1640.96   213.7 1647.12   222.3 1650.23
   251.2 1654.61   263.3 1657.83   275.4 1661.66   298.2 1667.42   345.8 1675.59
#Mann= 4 ,-1 , 0
       0     .06       0   107.6     .05       0   134.4    .045       0
   162.7     .05       0
Bank Sta=134.4,162.7
XS Rating Curve= 0 ,0
Exp/Cntr(USF)=0,0
Exp/Cntr=0.3,0.1

Type RM Length L Ch R = 1 ,5669    ,33.8,33.7,33.8
XS GIS Cut Line= 4
2447291.90745561 630784.836596272447187.57594403630731.145525979
2447098.49757741630680.5050846822446988.06480783630681.115210481
#Sta/Elev= 30
       0 1655.94     5.8 1651.65     8.2 1650.74    10.3 1650.06    19.3 1648.74
    23.8 1645.57    32.8 1637.15    37.3 1633.65    40.9 1632.31    76.6 1631.96
    82.9 1630.62   100.3  1629.6   109.3 1629.69   113.8 1630.25   118.3 1630.77
   122.9 1630.72     134 1627.34   136.7 1626.75   147.5 1625.94   153.3 1626.13
   159.7 1627.23   174.5 1631.37   191.9  1632.8   201.1 1634.63   214.9 1641.29
   221.2 1643.42   231.6 1648.26   243.6 1651.28   303.6 1664.46   330.2 1668.35
#Mann= 4 ,-1 , 0
       0     .06       0   113.8     .05       0     134    .045       0
   159.7     .05       0
#XS Ineff= 2 , 0
          119.99 1633.61
Permanent Ineff=
       F       F
Bank Sta=134,159.7
XS Rating Curve= 0 ,0
Exp/Cntr(USF)=0,0
Exp/Cntr=0.5,0.3

Type RM Length L Ch R = 1 ,5636    ,40.5,39.8,39.5
XS GIS Cut Line= 4
2447312.06934756 630762.546236622447160.83460689630677.292225292
2447124.07368819 630663.678171872446986.15113615630657.287345407
#Sta/Elev= 30
       0 1659.33     6.6 1656.04    10.7 1652.14    15.3 1647.07    19.9 1643.27
    24.5 1641.18    33.7 1639.84    38.3 1637.96    47.4 1631.61    50.6 1631.28
    56.6 1631.72    65.3 1631.61    84.2 1630.35    97.9 1630.49     127 1629.27
     1401626.604   147.5 1625.23     153 1624.97   163.5 1626.63   171.4 1628.92
   180.1 1630.66   188.6  1631.6   218.1  1633.5   226.2 1635.85   246.2 1644.53
   258.2  1648.7   284.8 1653.22   301.6 1657.92   314.2 1660.33   350.9 1664.13
#Mann= 4 ,-1 , 0
       0     .06       0     127     .05       0     140    .045       0
   163.5     .05       0
#XS Ineff= 2 , 0
             130 1629.81     173         1629.81
Permanent Ineff=
       F       F
Bank Sta=140,163.5
XS Rating Curve= 0 ,0
Exp/Cntr(USF)=0,0
Exp/Cntr=0.5,0.3

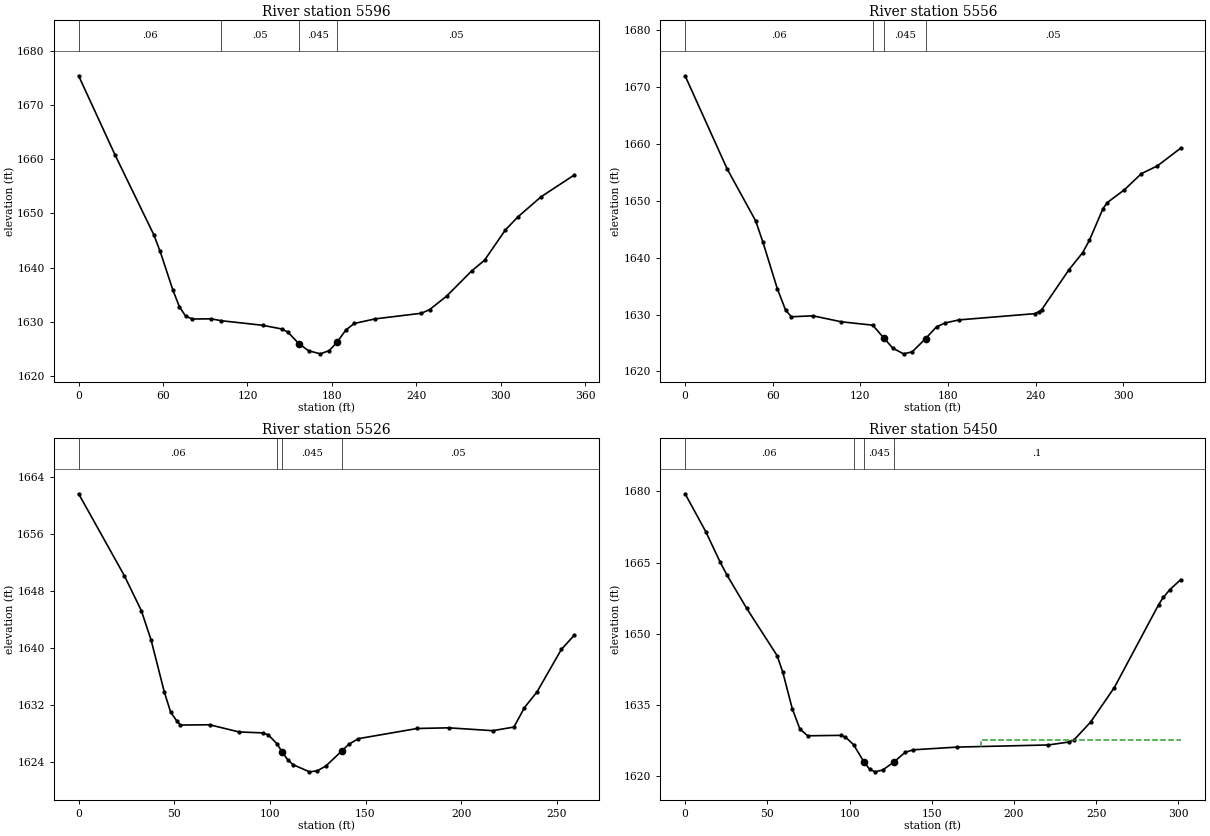
Type RM Length L Ch R = 1 ,5596    ,38.6,40,40.4
XS GIS Cut Line= 3
2447353.61733636630737.6944703532447177.03544566 630641.61472115
2447041.65744795630574.325332137
#Sta/Elev= 30
       0  1675.4      26 1660.73    53.4 1646.07    57.9 1643.01      67 1635.85
    71.6 1632.77    76.1 1631.03    80.9 1630.51    94.3 1630.54   101.5 1630.19
   130.8 1629.35   144.4 1628.67   148.7 1628.09   156.5 1625.97   163.4 1624.65
   171.8 1624.08   178.2 1624.69   183.61626.218     190  1628.5   195.9 1629.68
   210.7 1630.53   243.6 1631.57   249.5 1632.25   261.5 1634.72   279.4 1639.39
   288.5 1641.36   303.2 1646.91   312.2 1649.36   328.7 1653.07   352.2 1657.08
#Mann= 4 ,-1 , 0
       0     .06       0   101.5     .05       0   156.5    .045       0
   183.6     .05       0
Bank Sta=156.5,183.6
XS Rating Curve= 0 ,0
Exp/Cntr(USF)=0,0
Exp/Cntr=0.5,0.3

Type RM Length L Ch R = 1 ,5556    ,28.7,30.3,31.8
XS GIS Cut Line= 4
2447354.14011266630711.4671918722447270.69758471630652.401132762
2447160.06591844630582.0843957272447069.12293854630527.706119086
#Sta/Elev= 30
       0 1671.94    28.7 1655.63    48.3 1646.46    53.2 1642.79    63.1 1634.57
    68.8 1630.78    72.8 1629.61    87.5 1629.78   106.9 1628.73  128.451628.134
  136.09 1625.87   142.3 1624.08   149.6  1623.1   155.5 1623.45   164.7 1625.79
   172.2 1627.86     178 1628.52   187.5 1629.06   239.5 1630.16   242.4 1630.53
   244.2 1630.88   262.9  1637.9   272.1 1640.84   276.8 1643.03   286.1  1648.6
   289.1 1649.68   300.8 1651.92   312.4 1654.75   323.4 1656.12339.2799 1659.22
#Mann= 4 ,-1 , 0
       0     .06       0  128.45     .05       0  136.09    .045       0
   164.7     .05       0
#XS Ineff= 2 , 0
             128 1627.47     173         1627.47
Permanent Ineff=
       F       F
Bank Sta=136.09,164.7
XS Rating Curve= 0 ,0
Exp/Cntr(USF)=0,0
Exp/Cntr=0.5,0.3

Type RM Length L Ch R = 1 ,5526    ,76.9,75.7,74
XS GIS Cut Line= 3
2447344.41077052630678.776621377 2447226.1294818 630584.85228977
2447147.90282085630510.237668852
#Sta/Elev= 30
       0 1661.66    23.9 1650.16    32.8 1645.24    37.9 1641.11    44.8 1633.82
    48.1    1631    51.3 1629.76    53.2 1629.18    68.5 1629.22    83.9 1628.21
    96.3 1628.08    99.2 1627.79   103.6 1626.58   106.4 1625.42   109.3 1624.31
   112.1 1623.62   120.7 1622.61   124.7 1622.75   129.2 1623.41   137.8  1625.6
   141.3 1626.49   146.3 1627.27   177.1  1628.7   193.6 1628.79   216.5 1628.39
   227.6  1628.9   233.1 1631.63   239.7 1633.85   252.4  1639.8   259.1 1641.79
#Mann= 4 ,-1 , 0
       0     .06       0   103.6     .05       0   106.4    .045       0
   137.8     .05       0
Bank Sta=106.4,137.8
XS Rating Curve= 0 ,0
Exp/Cntr(USF)=0,0
Exp/Cntr=0.5,0.3

Type RM Length L Ch R = 1 ,5450    ,96.9,97,96.7
XS GIS Cut Line= 4
2447399.14282436630603.6481950842447323.20074836630559.583039876
2447222.88220353630505.2047632352447142.25234506630447.076260619
#Sta/Elev= 30
       0 1679.51    12.6 1671.52    21.3 1665.13    25.4 1662.44    37.5 1655.36
      56 1645.41    59.4 1641.94    65.2 1634.21    69.8 1630.01    74.5 1628.56
    94.5 1628.65    97.4 1628.32  102.431626.696  108.861622.998   112.3 1621.48
   115.6 1620.97   120.2 1621.37  126.821622.997   133.8 1625.08   138.8 1625.61
   165.4 1626.18   220.9 1626.63   233.2 1627.24   236.6 1627.74   246.5 1631.42
     261 1638.72   287.9 1656.15   290.8 1657.71   294.8 1659.35 301.308 1661.42
#Mann= 4 ,-1 , 0
       0     .06       0  102.43     .05       0  108.86    .045       0
  126.82      .1       0
#XS Ineff= 2 , 0
                          180.04         1627.75
Permanent Ineff=
       F       F
Bank Sta=108.86,126.82
XS Rating Curve= 0 ,0
Exp/Cntr(USF)=0,0
Exp/Cntr=0.3,0.1