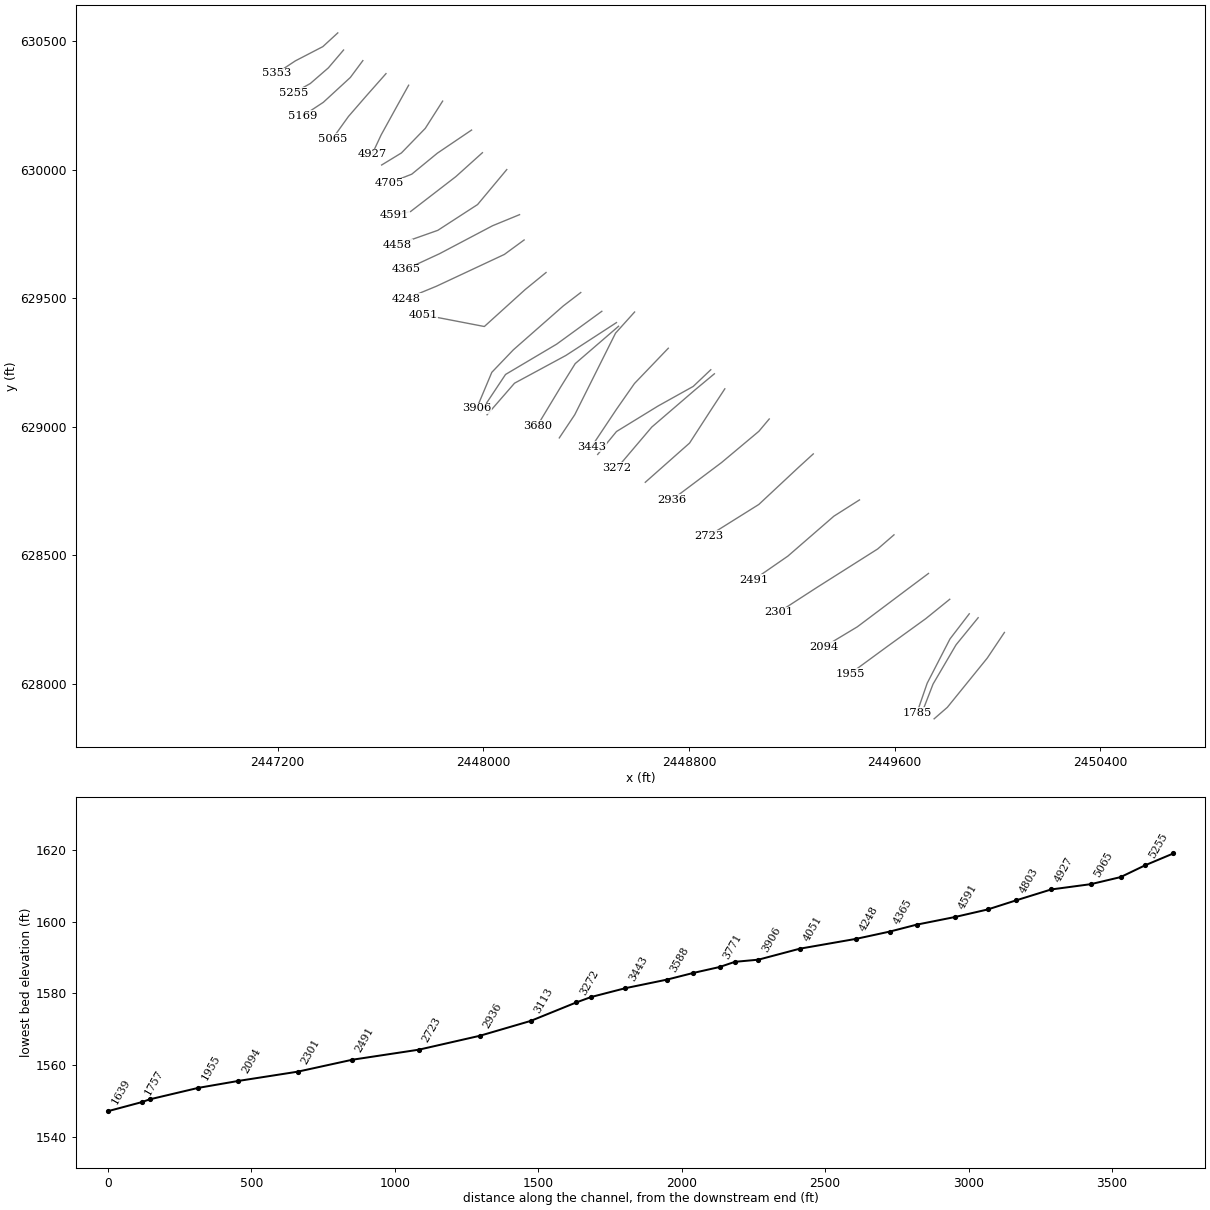
HEC-RAS study HAMMERRN.prj: HAMMERRN

--- HAMMERRN.g01 (geometry) --- (continued)

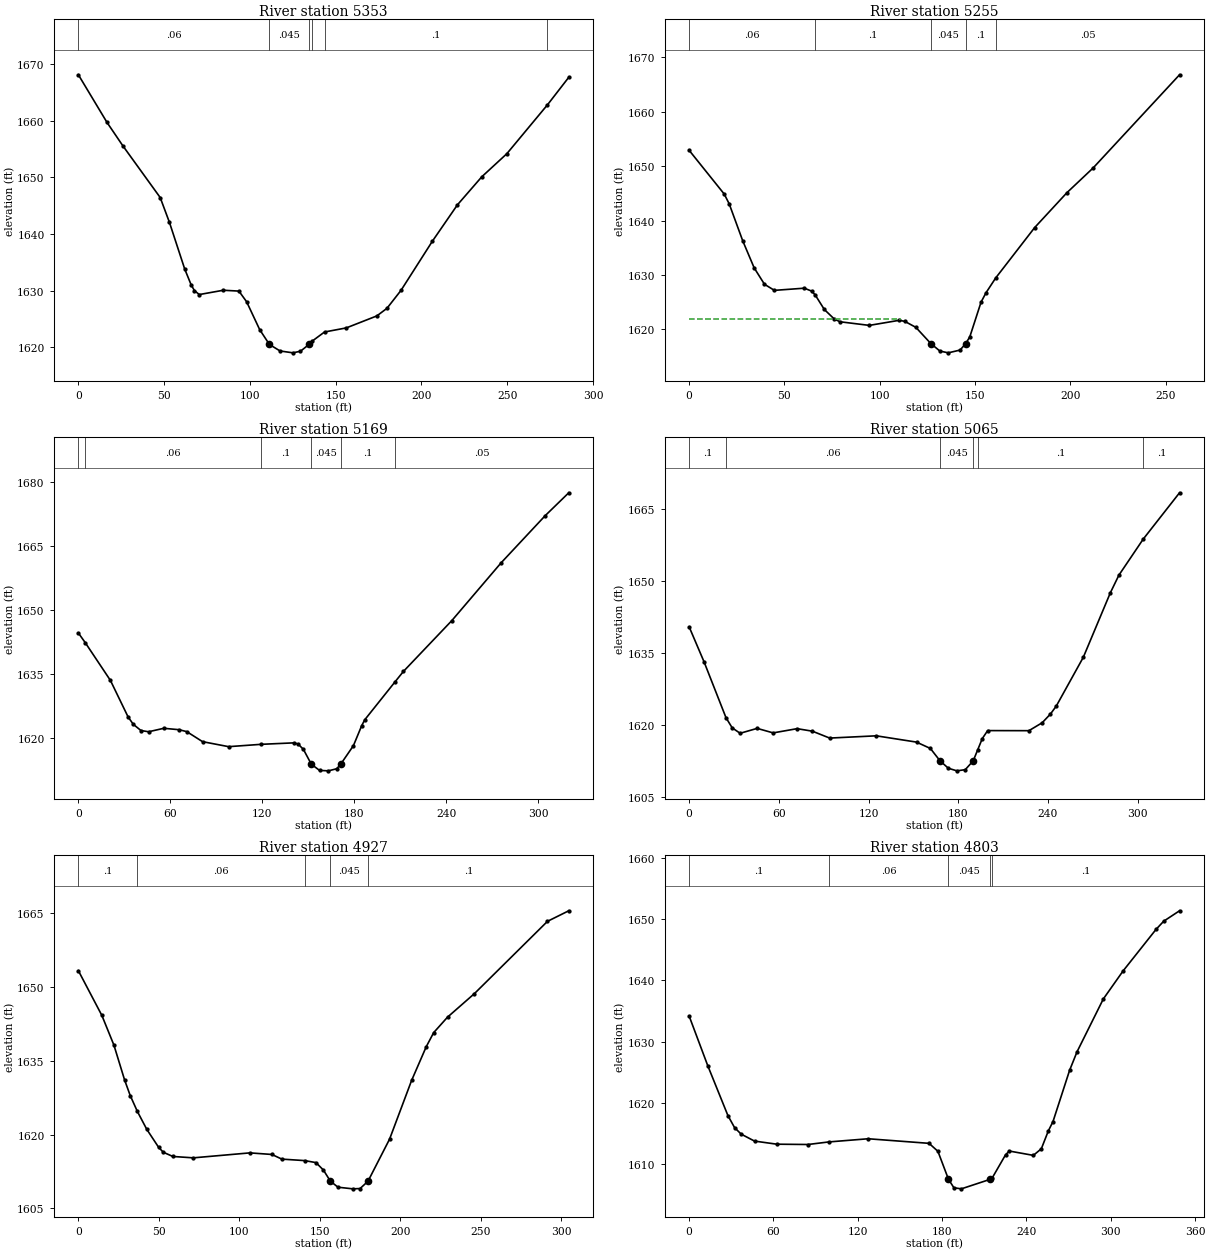
Type RM Length L Ch R = 1 ,5353    ,95.4,97.6,99.2
XS GIS Cut Line= 4
2447433.83241463630531.4563450622447375.70391202630478.015624915
2447268.82247172 630422.69979178 2447196.6306217630374.884410596
#Sta/Elev= 30
       0 1668.16    16.7 1659.73    25.9 1655.61    47.7 1646.45    53.1 1642.05
      62  1633.8    65.8 1630.97    67.7 1629.97    70.5 1629.29    84.5 1630.05
    93.6  1629.9    98.1 1628.01   105.7 1623.09  111.381620.463   117.6 1619.31
   125.1 1618.98   129.5 1619.27  134.461620.462   136.3 1621.05  143.511622.667
   156.2 1623.39     174 1625.51   179.9 1626.85   188.1 1630.03   206.4 1638.73
     221 1645.16   235.2 1650.12   249.8  1654.2   273.51662.852285.8991 1667.71
#Mann= 6 ,-1 , 0
       0     .06       0  111.38    .045       0  134.46     .06       0
   136.3      .1       0  143.51      .1       0   273.5     .05       0
Bank Sta=111.38,134.46
XS Rating Curve= 0 ,0
Exp/Cntr(USF)=0,0
Exp/Cntr=0.3,0.1

Type RM Length L Ch R = 1 ,5255    ,86.5,86.7,87
XS GIS Cut Line= 4
2447456.33377048630464.8898340022447397.26771137 630395.51065346
2447326.95097434630334.5694813632447263.19713276630298.942334598
#Sta/Elev= 30
       0 1652.89    18.4 1644.86      21 1643.07    28.1 1636.28    34.1 1631.31
    39.5  1628.3    44.7 1627.18    60.4 1627.58    64.2 1627.05   66.041626.379
    70.9 1623.67    76.2 1621.89    79.2 1621.41    94.5 1620.75   110.3 1621.69
   113.2 1621.47   118.9 1620.39  126.781617.407   131.5 1616.04   135.9 1615.71
   142.1 1616.22  145.051617.408   147.2 1618.65   153.1 1625.02   155.7 1626.74
  160.791629.464   181.2  1638.7   198.1  1645.1   211.9 1649.66257.1998 1666.76
#Mann= 5 ,-1 , 0
       0     .06       0   66.04      .1       0  126.78    .045       0
  145.05      .1       0  160.79     .05       0
#XS Ineff= 2 , 0
          110.48 1621.84
Permanent Ineff=
       F       F
Bank Sta=126.78,145.05
XS Rating Curve= 0 ,0
Exp/Cntr(USF)=0,0
Exp/Cntr=0.3,0.1

Type RM Length L Ch R = 1 ,5169    ,102,103.4,104.3
XS GIS Cut Line= 4
2447531.33828999630423.6373482742447482.58535231630358.008393708
  2447377.579025630261.4400748462447297.88672303630208.936911193
#Sta/Elev= 30
       0 1644.65    4.531642.367    20.9 1633.55    32.4 1625.02    35.8 1623.28
    40.8 1621.82    45.8 1621.53    55.7 1622.34    65.7 1622.01    70.7 1621.56
      81 1619.21      98 1618.04  119.121618.586   140.5 1618.93   143.3 1618.67
   146.8 1617.39  151.931613.938   157.3 1612.48   163.1 1612.38   168.5 1612.87
  171.111613.941   179.4 1618.28   184.8 1622.96   186.8 1624.34  206.681633.282
     212 1635.65   243.6 1647.56   275.7 1661.07   304.5 1672.13319.8484 1677.48
#Mann= 6 ,-1 , 0
       0      .1       0    4.53     .06       0  119.12      .1       0
  151.93    .045       0  171.11      .1       0  206.68     .05       0
Bank Sta=151.93,171.11
XS Rating Curve= 0 ,0
Exp/Cntr(USF)=0,0
Exp/Cntr=0.3,0.1

Type RM Length L Ch R = 1 ,5065    ,135.2,138.5,140.4
XS GIS Cut Line= 4
2447621.34371339630373.0092976092447542.58896791630283.941430698
2447475.08490036630206.1242417122447413.20617177630119.869044282
#Sta/Elev= 30
       0 1640.43      10 1633.12   24.661621.492    28.8 1619.38    34.1 1618.25
    45.5 1619.27    56.2 1618.33    72.2 1619.21    82.4 1618.69      94 1617.25
   125.2 1617.72   152.1 1616.41   161.4 1615.08  167.861612.498   173.4 1610.96
   179.1 1610.42   184.7 1610.66  190.021612.497  192.991614.761   196.1 1617.14
   199.7 1618.81   227.3 1618.79   236.2 1620.45   241.7 1622.26   245.6 1623.92
   263.7  1634.1   281.8 1647.55   287.5 1651.21  303.76 1658.72328.0637 1668.38
#Mann= 6 ,-1 , 0
       0      .1       0   24.66     .06       0  167.86    .045       0
  190.02     .06       0  192.99      .1       0  303.76      .1       0
Bank Sta=167.86,190.02
XS Rating Curve= 0 ,0
Exp/Cntr(USF)=0,0
Exp/Cntr=0.3,0.1

Type RM Length L Ch R = 1 ,4927    ,124.8,123.2,118.6
XS GIS Cut Line= 4
2447709.47402381630328.0065859062447663.53375561630245.501614452
2447602.59258352630134.8699481832447566.96543675630058.927872185
#Sta/Elev= 30
       0 1653.35    14.6 1644.24    22.1 1638.18    28.7 1631.12    32.2 1627.94
   36.661624.688    42.5 1621.05    49.9 1617.37    52.8 1616.38    58.7 1615.53
    71.4 1615.25   106.5 1616.26   120.2 1615.94   126.4 1614.99  140.57 1614.69
   147.6 1614.28   152.2 1612.77  156.571610.489   161.3 1609.27   170.5 1608.94
     175    1609  179.911610.488   193.3 1619.05     207 1631.01   216.1 1637.88
   220.7 1640.74   229.3 1643.89     246 1648.68   291.4  1663.4304.6227 1665.55
#Mann= 5 ,-1 , 0
       0      .1       0   36.66     .06       0  140.57      .1       0
  156.57    .045       0  179.91      .1       0
Bank Sta=156.57,179.91
XS Rating Curve= 0 ,0
Exp/Cntr(USF)=0,0
Exp/Cntr=0.3,0.1

Type RM Length L Ch R = 1 ,4803    ,98.4,98,94.5
XS GIS Cut Line= 4
2447841.66948943630266.1278573152447774.16542188630160.183973516
2447681.34732899630064.553211148 2447604.4676965630017.675386458
#Sta/Elev= 30
       0 1634.17    13.3 1626.01    27.6 1617.87    32.3 1615.91      37 1614.84
    46.5  1613.7    62.4 1613.19    84.5 1613.14   99.441613.562   127.4 1614.08
   170.7 1613.33     177 1612.03  184.511607.451   188.4 1606.05   193.7 1605.88
  214.331607.448  215.771607.716   225.1 1611.44   227.8 1612.07   244.9 1611.36
   250.6 1612.44   255.6 1615.38   258.9  1616.9   270.7 1625.28     276 1628.32
   294.7 1636.97   308.8 1641.57   332.2 1648.36   337.7 1649.71348.9348 1651.41
#Mann= 5 ,-1 , 0
       0      .1       0   99.44     .06       0  184.51    .045       0
  214.33     .06       0  215.77      .1       0
Bank Sta=184.51,214.33
XS Rating Curve= 0 ,0
Exp/Cntr(USF)=0,0
Exp/Cntr=0.3,0.1

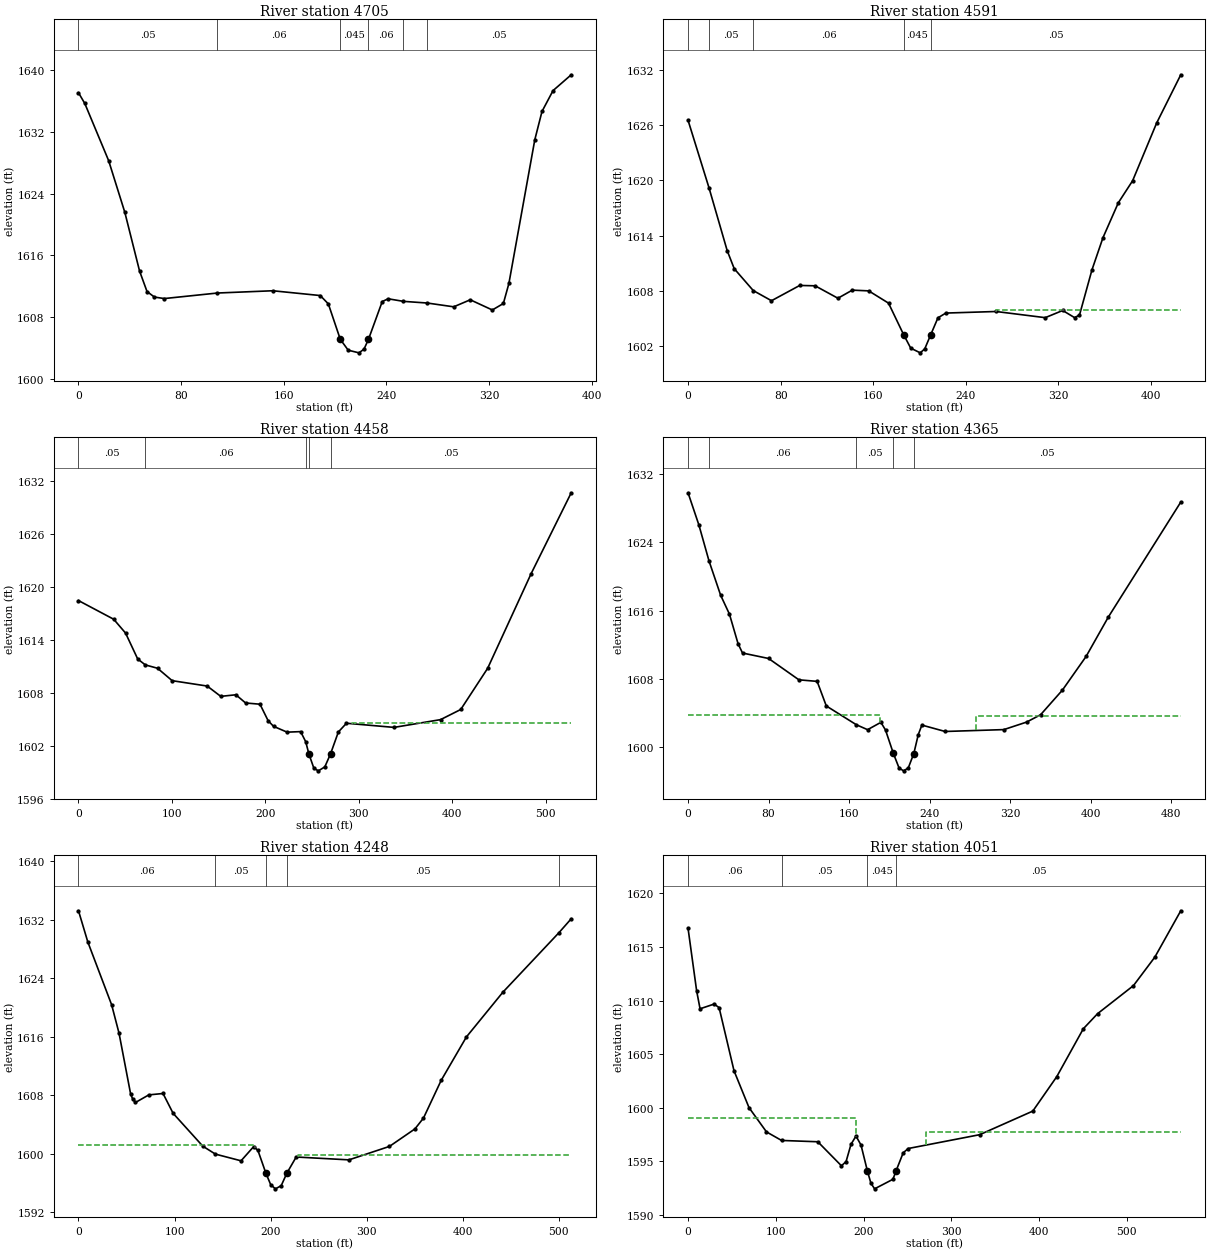
Type RM Length L Ch R = 1 ,4705    ,114.9,114.6,114.2
XS GIS Cut Line= 4
2447954.17626869630153.6210780592447821.04324657630063.615654654
2447721.66225823629982.0482396932447633.53194781629947.358649422
#Sta/Elev= 30
       0 1637.05     4.9 1635.67    23.5 1628.26    36.1 1621.57    47.6 1613.96
    53.4 1611.31    59.2 1610.59    66.9  1610.4  108.321611.117   151.4 1611.41
   188.4 1610.79   194.7 1609.71  204.021605.117   210.2 1603.71   218.6 1603.37
   222.5 1603.85  225.981605.118   236.7 1610.01   241.3 1610.37  253.191610.037
  271.84 1609.82   292.4 1609.33   305.3 1610.24   322.5 1608.92   331.1 1609.76
   335.4 1612.35   355.6 1630.97   361.2 1634.63   369.8 1637.33383.9829 1639.38
#Mann= 6 ,-1 , 0
       0     .05       0  108.32     .06       0  204.02    .045       0
  225.98     .06       0  253.19      .1       0  271.84     .05       0
Bank Sta=204.02,225.98
XS Rating Curve= 0 ,0
Exp/Cntr(USF)=0,0
Exp/Cntr=0.3,0.1

Type RM Length L Ch R = 1 ,4591    ,134.4,133,132.3
XS GIS Cut Line= 4
2447996.36631091630065.4907676412447893.23509659629972.672674755
2447716.97447576629836.7269831532447654.15819067629822.663635746
#Sta/Elev= 30
       0 1626.52   18.181619.155    33.8 1612.37    39.9  1610.4   56.341608.024
    72.1 1606.92    96.5 1608.58   109.8 1608.54   129.5 1607.19   141.9 1608.07
   156.1 1607.99   173.2 1606.66  186.211603.248   192.4 1601.77   200.6 1601.26
   204.5 1601.69  209.751603.249   215.9 1605.06   222.7 1605.58   266.1 1605.75
   308.6 1605.08   323.7 1605.86   333.9 1605.09   338.2 1605.36     349 1610.28
   358.5 1613.77   371.8 1617.57   384.1 1619.95   404.9 1626.23425.7163 1631.46
#Mann= 5 ,-1 , 0
       0      .1       0   18.18     .05       0   56.34     .06       0
  186.21    .045       0  209.75     .05       0
#XS Ineff= 2 , 0
                          266.12         1605.94
Permanent Ineff=
       F       F
Bank Sta=186.21,209.75
XS Rating Curve= 0 ,0
Exp/Cntr(USF)=0,0
Exp/Cntr=0.3,0.1

Type RM Length L Ch R = 1 ,4458    ,94.3,93.2,91.9
XS GIS Cut Line= 4
2448091.05951679629999.8618130752447977.61518104629863.916121474
2447822.91835956629763.5975766372447666.34642509629708.281743502
#Sta/Elev= 30
       0 1618.46    37.7 1616.34    50.4 1614.77    63.4 1611.83   71.53 1611.16
    84.6 1610.78   100.3 1609.37   137.8 1608.76   152.3 1607.59   168.5 1607.77
   178.9 1606.84   194.3  1606.7     203 1604.83   208.8 1604.19   223.3 1603.53
   237.8 1603.59  243.261602.444  246.61 1601.07     252 1599.43   256.8 1599.14
   263.7 1599.59  269.85 1601.07   278.2 1603.55   286.9 1604.54   337.8 1604.07
   387.6 1604.95   409.2  1606.1     438 1610.77   484.6 1621.52527.4949 1630.69
#Mann= 5 ,-1 , 0
       0     .05       0   71.53     .06       0  243.26     .05       0
  246.61    .045       0  269.85     .05       0
#XS Ineff= 2 , 0
                             293         1604.59
Permanent Ineff=
       F       F
Bank Sta=246.61,269.85
XS Rating Curve= 0 ,0
Exp/Cntr(USF)=0,0
Exp/Cntr=0.3,0.1

Type RM Length L Ch R = 1 ,4365    ,117.3,117,116.5
XS GIS Cut Line= 4
2448140.75001096629824.5387487342448035.74368365629781.411150019
2447829.48125502629672.6545967382447700.09845887629612.650981135
#Sta/Elev= 30
       0 1629.79    10.8 1626.01   20.84  1621.8    32.4 1617.78    41.1 1615.58
    49.7  1612.1    54.1 1611.02      80 1610.38   110.1 1607.88   128.2  1607.7
   137.3 1604.82  167.191602.617   178.3 1602.04   191.5  1602.9   196.1    1602
  203.921599.252   209.6 1597.54   214.1 1597.22   218.7 1597.56  224.211599.248
   228.6 1601.45   232.2 1602.58   255.3 1601.83   313.6 1602.05   336.2 1602.93
   350.1 1603.79   371.8 1606.68   395.3 1610.62   417.4 1615.24489.3159  1628.7
#Mann= 5 ,-1 , 0
       0      .1       0   20.84     .06       0  167.19     .05       0
  203.92    .045       0  224.21     .05       0
#XS Ineff= 2 , 0
          190.67 1603.72  286.01         1603.59
Permanent Ineff=
       F       F
Bank Sta=203.92,224.21
XS Rating Curve= 0 ,0
Exp/Cntr(USF)=0,0
Exp/Cntr=0.3,0.1

Type RM Length L Ch R = 1 ,4248    ,193.6,197,202.7
XS GIS Cut Line= 4
2448158.56358434629726.0953168852448081.68395185629669.841927257
 2447817.2930206629546.0844700752447701.03601536629498.269088891
#Sta/Elev= 30
       0  1633.2     9.7 1628.94    34.5 1620.35    42.2 1616.47    54.3 1608.14
    56.5 1607.45    59.3    1607    73.2 1608.04      88 1608.23    98.5 1605.52
   129.4 1601.03  142.511599.946   169.2 1599.03   182.4 1600.98   186.8 1600.44
  195.031597.348   200.1 1595.76     205  1595.2     211 1595.63  216.911597.348
   226.6 1599.55   281.5 1599.16   323.7    1601   350.2 1603.39   359.1 1604.87
   377.5 1610.02   403.8 1615.96   441.8 1622.08  500.261630.227512.8904 1632.11
#Mann= 5 ,-1 , 0
       0     .06       0  142.51     .05       0  195.03    .045       0
  216.91     .05       0  500.26      .1       0
#XS Ineff= 2 , 0
          183.54 1601.16  228.74         1599.76
Permanent Ineff=
       F       F
Bank Sta=195.03,216.91
XS Rating Curve= 0 ,0
Exp/Cntr(USF)=0,0
Exp/Cntr=0.3,0.1

Type RM Length L Ch R = 1 ,4051    ,144.4,144.3,143.9
XS GIS Cut Line= 4
2448243.88122528629599.5251902212448162.31381032629532.958679161
2448003.86676286629389.5125356092447765.72741344629435.452803806
#Sta/Elev= 30
       0 1616.75     9.8 1610.91    13.7 1609.24    29.7 1609.68    35.4 1609.35
    52.4 1603.46    69.5 1600.02    89.4 1597.76  106.581596.963   147.9 1596.84
   174.8  1594.6   180.1 1594.99   185.7  1596.6   191.4 1597.37   197.1 1596.54
  204.361594.131   208.4 1592.98   212.6 1592.45   233.5 1593.34   237.11594.131
   245.2 1595.81   250.9 1596.21   332.4  1597.5   392.9  1599.7   420.2 1602.91
   450.5 1607.38   466.8 1608.79   507.6  1611.4     532 1614.06561.5464 1618.38
#Mann= 4 ,-1 , 0
       0     .06       0  106.58     .05       0  204.36    .045       0
   237.1     .05       0
#XS Ineff= 2 , 0
          191.89 1599.05   271.6         1597.75
Permanent Ineff=
       F       F
Bank Sta=204.36,237.1
XS Rating Curve= 0 ,0
Exp/Cntr(USF)=0,0
Exp/Cntr=0.3,0.1

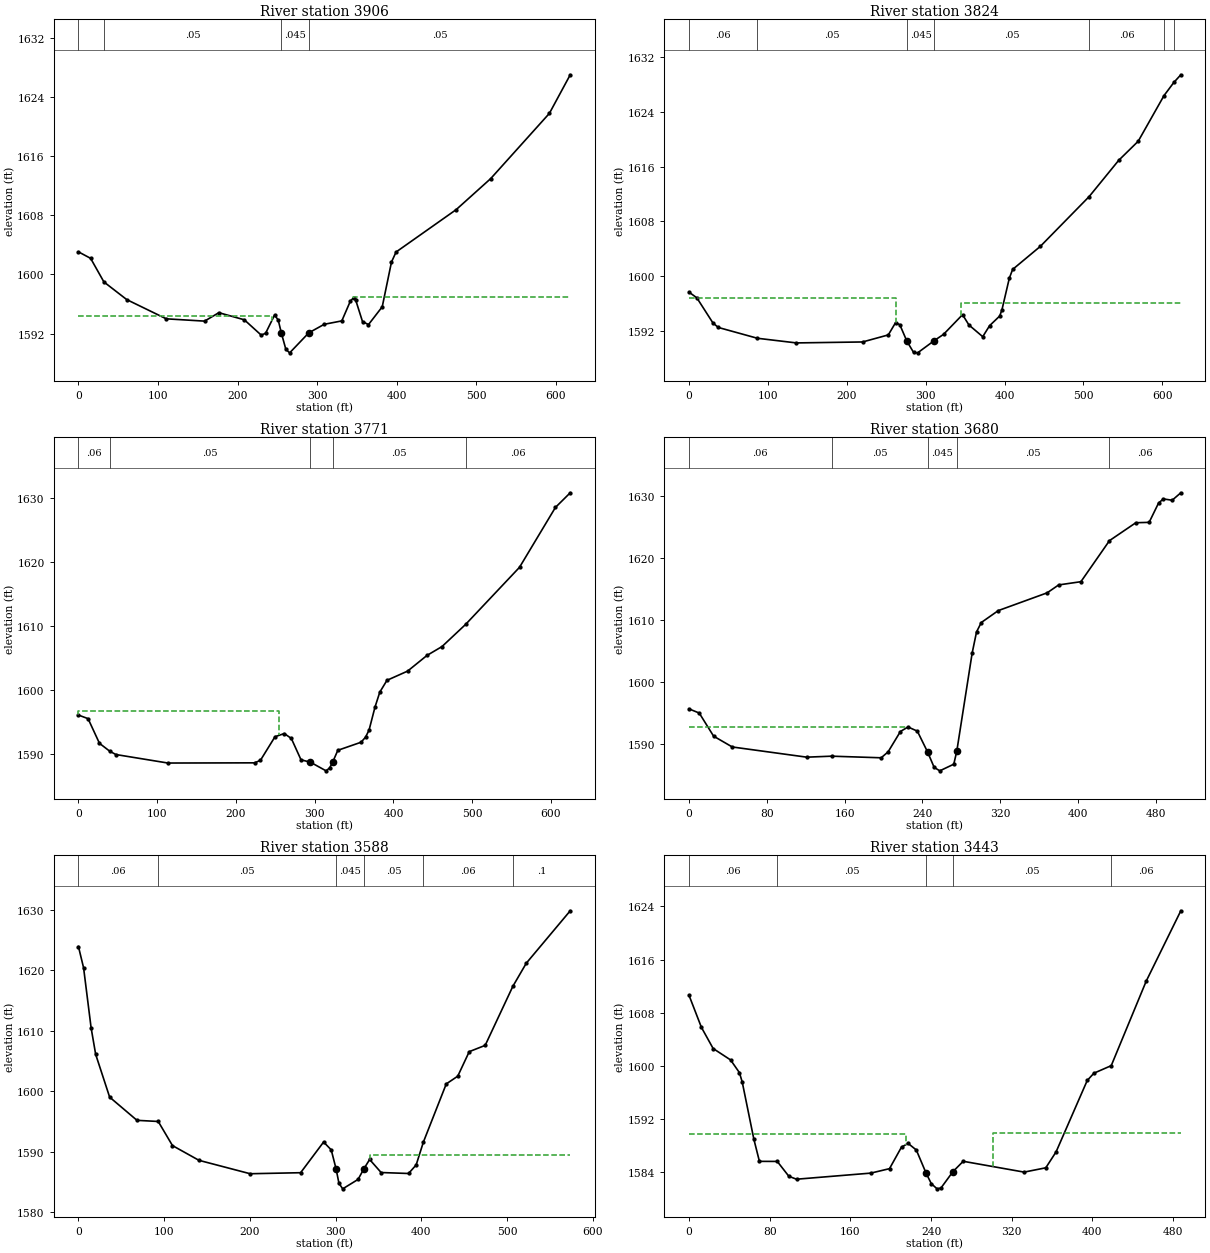
Type RM Length L Ch R = 1 ,3906    ,84.1,81.9,77.4
XS GIS Cut Line= 5
2448378.88936038629521.7080012362448310.44773634629469.204837583
2448116.37354212629298.5695557112448032.93101417629211.376801787
2447973.86495506629070.743327716
#Sta/Elev= 30
       0 1603.05    15.3 1602.17   31.99 1598.98    60.7 1596.59   110.4 1593.99
   158.5 1593.68   176.4 1594.82   208.4 1593.86   229.7 1591.78   235.2 1592.05
   246.4  1594.5     251 1593.83   254.9 1592.09   260.6 1589.86   265.4 1589.39
   289.41592.094   308.8 1593.25   330.9 1593.71   341.5 1596.35   345.6 1596.85
   348.4 1596.51   356.9 1593.62   364.4 1593.21   381.7 1595.62   393.3 1601.67
   399.1 1603.03   474.6 1608.76     518 1612.96   591.7 1621.78617.9012    1627
#Mann= 4 ,-1 , 0
       0     .06       0   31.99     .05       0   254.9    .045       0
   289.4     .05       0
#XS Ineff= 2 , 0
          242.81 1594.37   345.3         1596.92
Permanent Ineff=
       F       F
Bank Sta=254.9,289.4
XS Rating Curve= 0 ,0
Exp/Cntr(USF)=0,0
Exp/Cntr=0.5,0.3

Type RM Length L Ch R = 1 ,3824    ,54.7,53.2,54.4
XS GIS Cut Line= 4
 2448460.8008924629448.7201459892448285.04118878629320.894906995
2448086.31288753629203.0560147972447989.44532361629057.255351569
#Sta/Elev= 30
       0 1597.66     9.9 1596.83    30.3 1593.16    37.1  1592.5   86.65 1590.92
   136.1 1590.24     220 1590.38   252.6 1591.41   261.8  1593.2   267.2  1592.9
   276.2 1590.48   284.7 1588.84   289.8 1588.79     311 1590.59   322.6 1591.49
   346.7 1594.37   354.8 1592.86   372.3 1591.15     381 1592.76   393.8 1594.17
   396.7  1595.1     406  1599.7   410.2 1600.98   445.3 1604.35  507.271611.638
   544.6 1616.92   569.4 1619.72  602.121626.395  614.69 1628.33   623.4 1629.43
#Mann= 7 ,-1 , 0
       0     .06       0   86.65     .05       0   276.2    .045       0
     311     .05       0  507.27     .06       0  602.12     .05       0
  614.69     .06       0
#XS Ineff= 2 , 0
          262.98 1596.78  345.02          1596.1
Permanent Ineff=
       F       F
Bank Sta=276.2,311
XS Rating Curve= 0 ,0
Exp/Cntr(USF)=0,0
Exp/Cntr=0.5,0.3

Type RM Length L Ch R = 1 ,3771    ,79.7,91.7,94.7
XS GIS Cut Line= 4
2448517.72306914629404.7802200852448320.99203725629276.954981091
2448121.26510132629169.102435689 2448014.4111906629046.270370093
#Sta/Elev= 30
       0 1596.07    12.2 1595.51    26.7 1591.65   39.631590.429    47.5  1589.9
   113.6 1588.57   223.7  1588.6   231.1    1589   249.6 1592.69   261.4 1593.18
   270.3 1592.41   282.6 1589.07   294.4 1588.71   314.4 1587.35     319 1587.82
   323.1  1588.8   329.3 1590.56   358.8 1591.82   364.5 1592.61     369 1593.73
   376.5 1597.31   382.6 1599.65   391.7  1601.5   417.9 1602.94   442.6  1605.4
   461.6 1606.78  491.491610.233     560 1619.17   605.6 1628.53   624.4 1630.82
#Mann= 5 ,-1 , 0
       0     .06       0   39.63     .05       0   294.4    .045       0
   323.1     .05       0  491.49     .06       0
#XS Ineff= 2 , 0
          254.55 1596.73
Permanent Ineff=
       F       F
Bank Sta=294.4,323.1
XS Rating Curve= 0 ,0
Exp/Cntr(USF)=0,0
Exp/Cntr=0.5,0.3

Type RM Length L Ch R = 1 ,3680    ,89.8,91.7,92.6
XS GIS Cut Line= 4
2448525.88674966 629390.509313222448357.22844821629245.152487628
2448300.63914969629154.1657723712448209.65243444629003.260976336
#Sta/Elev= 30
       0 1595.67    10.5    1595    25.3 1591.28    44.5 1589.54   121.1  1587.9
   146.6 1588.06   197.7  1587.8   204.8 1588.75   217.5 1592.03   225.3 1592.76
   234.9 1592.09   245.51588.715   252.2 1586.26     258  1585.7   272.4 1586.77
   275.5 1588.87   291.3 1604.65   295.8 1608.05   300.7 1609.57   318.2 1611.49
   368.5 1614.35   380.3 1615.62   403.2 1616.14   432.6 1622.75   459.7 1625.63
   473.4 1625.69   483.1  1628.8     488 1629.46   497.1 1629.25     506 1630.45
#Mann= 5 ,-1 , 0
       0     .06       0   146.6     .05       0   245.5    .045       0
   275.5     .05       0   432.6     .06       0
#XS Ineff= 2 , 0
          223.39 1592.74
Permanent Ineff=
       F       F
Bank Sta=245.5,275.5
XS Rating Curve= 0 ,0
Exp/Cntr(USF)=0,0
Exp/Cntr=0.3,0.1

Type RM Length L Ch R = 1 ,3588    ,147.3,145.3,143.2
XS GIS Cut Line= 4
2448588.21910348629445.9048224962448514.14056569629363.723944644
2448355.56619575629046.5752047652448295.37738381628956.291986843
#Sta/Elev= 30
       0 1623.95       6 1620.43    14.8 1610.47    20.1  1606.1    36.4 1599.02
    68.3 1595.18   93.091594.991   109.7    1591   140.6 1588.56   200.3 1586.34
   259.2 1586.51     286 1591.59   294.9 1590.29   300.6 1587.12   303.9 1584.76
   308.3 1583.84   326.2  1585.4   332.9 1587.13   339.7  1588.7   353.1 1586.54
   385.1 1586.38     394  1587.8  402.431591.591   429.1 1601.21   442.5 1602.49
   455.9 1606.55   474.5 1607.59   506.81617.371   522.5  1621.2573.7305 1629.87
#Mann= 6 ,-1 , 0
       0     .06       0   93.09     .05       0   300.6    .045       0
   332.9     .05       0  402.43     .06       0   506.8      .1       0
#XS Ineff= 2 , 0
          285.48 1591.37  339.92         1589.41
Permanent Ineff=
       F       F
Bank Sta=300.6,332.9
XS Rating Curve= 0 ,0
Exp/Cntr(USF)=0,0
Exp/Cntr=0.3,0.1

Type RM Length L Ch R = 1 ,3443    ,123.5,118.8,114.1
XS GIS Cut Line= 4
2448719.27342712629305.0185922972448587.73591388629167.843757059
2448518.20894259629068.2510684612448420.49536133628921.680696563
#Sta/Elev= 30
       0  1610.6    12.3 1605.77    23.9 1602.59    41.2 1600.87      50 1598.95
    52.8 1597.51    64.3 1588.92    69.8 1585.59    87.5 1585.58      99 1583.34
   106.6  1582.9   180.3 1583.82   198.8 1584.49   210.7 1587.74   217.3 1588.29
   225.4  1587.3   235.1 1583.81   240.3 1582.22     246 1581.45   249.8 1581.57
   261.7 1584.04   271.9  1585.6   332.3 1583.97   353.8 1584.62     364 1587.02
   394.9 1597.78   401.5 1598.87   418.7 1600.01   453.4 1612.75   487.7 1623.34
#Mann= 5 ,-1 , 0
       0     .06       0    87.5     .05       0   235.1    .045       0
   261.7     .05       0   418.7     .06       0
#XS Ineff= 2 , 0
          214.68 1589.78  301.78         1589.87
Permanent Ineff=
       F       F
Bank Sta=235.1,261.7
XS Rating Curve= 0 ,0
Exp/Cntr(USF)=0,0
Exp/Cntr=0.5,0.3

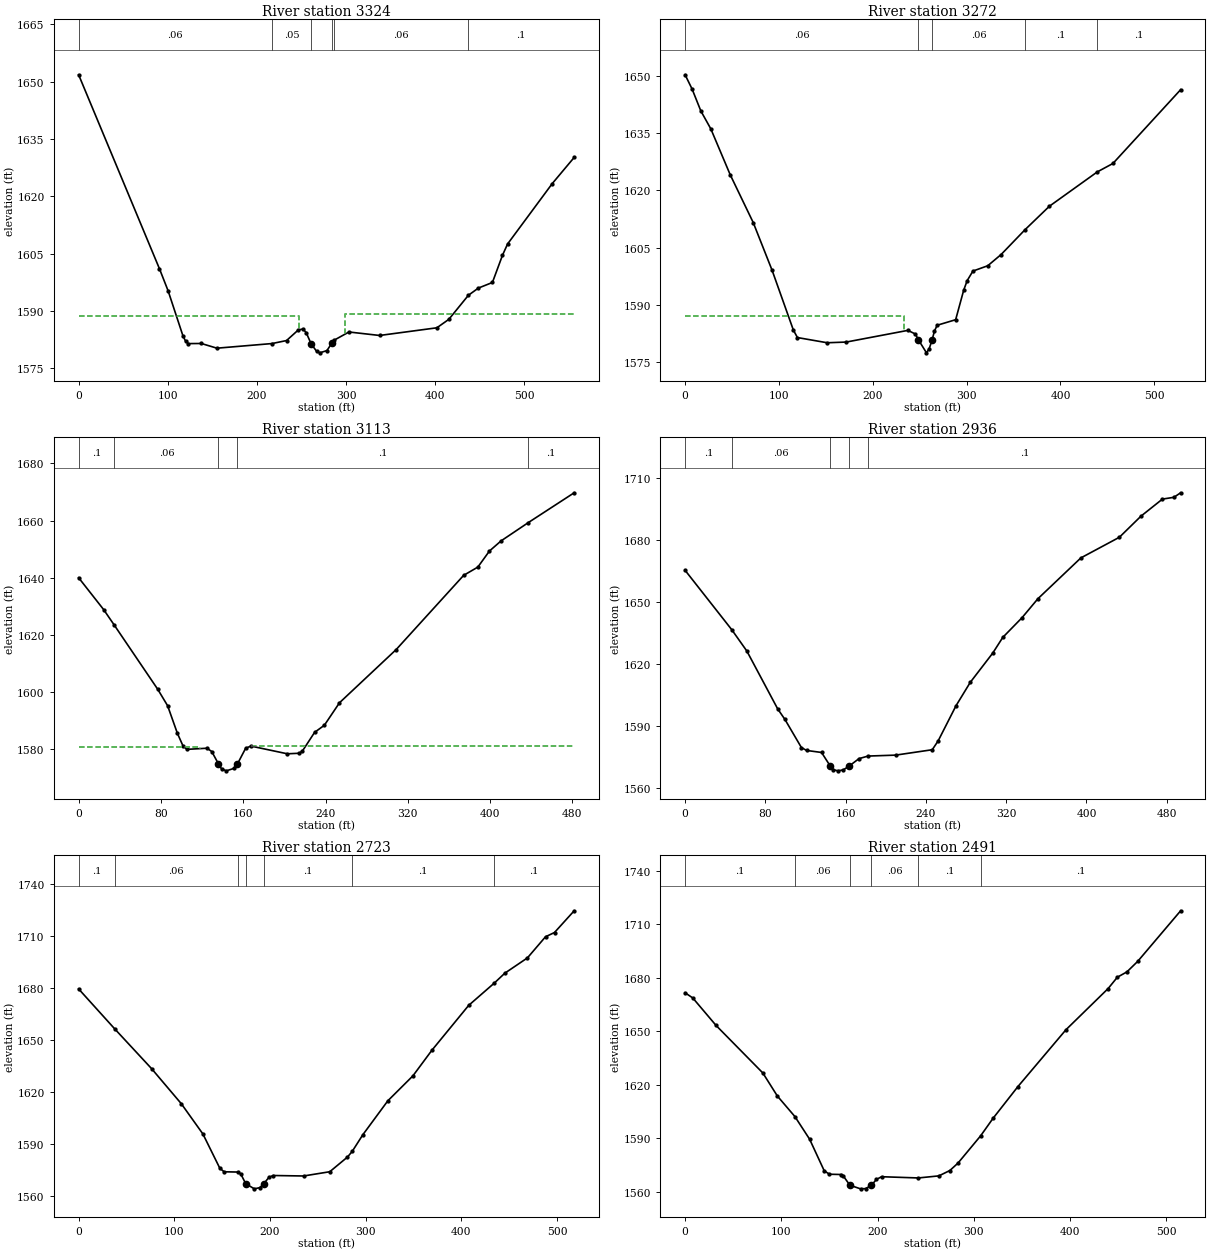
Type RM Length L Ch R = 1 ,3324    ,48.9,51.6,54.6
XS GIS Cut Line= 5
 2448884.5332546629221.3542548442448816.24210259629156.535534285
2448680.20214489629080.7571730132448517.80760957628981.105980888
2448444.60704252628891.912012628
#Sta/Elev= 30
       0 1651.83    90.7    1601   100.4 1595.22     117 1583.45     120 1582.04
   122.9 1581.42   137.6 1581.45   155.1 1580.22  216.84 1581.43   233.2 1582.22
   246.4    1585   251.6 1585.24   255.2 1584.31   260.8 1581.35   266.8 1579.43
   270.4    1579   278.5 1579.59  284.031581.565  286.611582.321   303.2 1584.46
   337.6 1583.55   401.8 1585.56   415.2 1587.77  437.211594.091   448.4 1595.97
   464.1 1597.43   475.4 1604.56   481.1 1607.51   531.2 1623.33555.7941 1630.18
#Mann= 6 ,-1 , 0
       0     .06       0  216.84     .05       0   260.8    .045       0
  284.03     .05       0  286.61     .06       0  437.21      .1       0
#XS Ineff= 2 , 0
          246.91 1588.76  298.77          1589.1
Permanent Ineff=
       F       F
Bank Sta=260.8,284.03
XS Rating Curve= 0 ,0
Exp/Cntr(USF)=0,0
Exp/Cntr=0.5,0.3

Type RM Length L Ch R = 1 ,3272    ,158.1,159.3,160.2
XS GIS Cut Line= 4
2448898.57358442629205.6287285762448825.98814818629145.345908649
2448654.98178145628998.3296437242448520.26813284628839.625893304
#Sta/Elev= 30
       0 1650.27     7.5 1646.51    16.8 1640.79    27.4 1636.12    48.1 1624.09
    72.6 1611.59    92.7 1599.11   115.4 1583.44   119.7  1581.5   151.4 1580.14
   171.7 1580.32   237.4 1583.38   245.4 1582.42   248.7 1580.89   257.2  1577.5
   260.1 1578.58  263.051580.745   265.7 1583.19   268.6 1584.72   288.3 1586.17
   296.9 1593.93   300.6 1596.41   306.7  1598.9   322.5 1600.29   336.7 1603.22
   362.11609.695   388.2 1615.87  439.261624.857   455.9 1627.06528.0386 1646.37
#Mann= 5 ,-1 , 0
       0     .06       0   248.7    .045       0  263.05     .06       0
   362.1      .1       0  439.26      .1       0
#XS Ineff= 2 , 0
          233.74 1587.27
Permanent Ineff=
       F       F
Bank Sta=248.7,263.05
XS Rating Curve= 0 ,0
Exp/Cntr(USF)=0,0
Exp/Cntr=0.5,0.3

Type RM Length L Ch R = 1 ,3113    ,179.4,176.8,173.2
XS GIS Cut Line= 4
2448939.17221825629147.191301096  2448889.961753629072.145341595
2448801.99804637 628936.201431352448629.76141801628783.648989086
#Sta/Elev= 30
       0 1639.98    24.3 1628.83   34.771623.325    76.9 1600.91    86.5 1595.15
      96 1585.49   101.7 1580.88   105.5 1579.87   124.8 1580.26   129.4 1579.11
  135.951574.776   138.9 1573.04   143.6 1572.34   150.8 1573.18  154.421574.771
   162.4 1580.27   167.5 1581.01   202.9 1578.31   214.5  1578.5   217.4 1579.19
   229.4 1585.82   238.9 1588.31   253.6 1596.19   308.7 1614.82   374.3 1640.82
   388.1 1643.71   399.4 1649.35   410.7 1652.89  437.26 1659.32481.7444 1669.74
#Mann= 5 ,-1 , 0
       0      .1       0   34.77     .06       0  135.95    .045       0
  154.42      .1       0  437.26      .1       0
#XS Ineff= 2 , 0
          118.28 1580.53  168.01         1580.98
Permanent Ineff=
       F       F
Bank Sta=135.95,154.42
XS Rating Curve= 0 ,0
Exp/Cntr(USF)=0,0
Exp/Cntr=0.3,0.1

Type RM Length L Ch R = 1 ,2936    ,212.4,213,213.5
XS GIS Cut Line= 4
2449111.88896929629029.9046713232449071.38652876628981.808023191
2448926.25278352628860.3007015942448733.02239015628715.166956353
#Sta/Elev= 30
       0 1665.46   46.571636.616    61.5 1626.34    92.3 1598.23    99.5 1593.13
   115.9 1579.51   121.1  1578.1     136 1577.12   144.71570.501   147.8 1568.72
   152.4 1568.21   157.6 1568.66  163.411570.502   173.3 1574.13   182.31575.376
   209.8 1575.83   246.3 1578.45   252.2 1582.76     270  1599.8   284.2 1611.14
   306.6 1625.33   316.6 1632.94   335.7 1642.45   351.6 1651.69   394.4 1671.48
   432.8  1681.5   454.3 1691.73   475.7 1700.01   487.1 1700.87493.8258 1703.07
#Mann= 5 ,-1 , 0
       0      .1       0   46.57     .06       0   144.7    .045       0
  163.41     .06       0   182.3      .1       0
Bank Sta=144.7,163.41
XS Rating Curve= 0 ,0
Exp/Cntr(USF)=0,0
Exp/Cntr=0.3,0.1

Type RM Length L Ch R = 1 ,2723    ,231.4,232,231.4
XS GIS Cut Line= 4
2449283.18054071628894.0527353712449224.95828245628840.893282172
2449071.38652876 628697.447138622448877.31233454628575.939817023
#Sta/Elev= 30
       0 1679.44   37.691656.456    76.2 1633.58   107.3 1613.36   129.9 1595.92
   147.6 1576.17   152.1 1574.15  166.45    1574   169.6  1572.8  174.651567.282
   183.7 1564.33   189.4 1565.03   193.51567.281     199 1571.01   203.5 1572.01
   235.1 1571.73   262.5 1574.18     281 1582.63  286.021585.942   297.1 1595.51
   323.2 1615.03   349.4 1629.39   369.2  1644.1   407.7 1669.98  434.451682.807
   445.5 1688.52   469.1 1697.32     488 1709.48   497.4 1711.94517.9589 1724.45
#Mann= 7 ,-1 , 0
       0      .1       0   37.69     .06       0  166.45      .1       0
  174.65    .045       0   193.5      .1       0  286.02      .1       0
  434.45      .1       0
Bank Sta=174.65,193.5
XS Rating Curve= 0 ,0
Exp/Cntr(USF)=0,0
Exp/Cntr=0.3,0.1

Type RM Length L Ch R = 1 ,2491    ,191.5,189.8,187.9
XS GIS Cut Line= 4
2449462.91012057628715.1669563532449363.34162093628651.881893022
2449184.45584191628496.6225376482449052.82291018 628405.49204645
#Sta/Elev= 30
       0 1671.52       8  1668.6    32.2 1653.18    80.8 1626.52    95.9 1613.58
  114.121602.066   129.4 1589.37   144.6 1571.63     150 1569.72   162.2 1569.57
   164.5 1568.68  171.241563.562   182.3 1561.53   187.6 1561.67  193.69 1563.56
   198.8 1566.82   204.2 1568.33  242.371567.638   263.7  1568.8   275.1  1571.8
   283.6 1575.98  307.121591.277     320 1601.09   345.9 1618.93   395.8  1650.8
   439.6 1673.89   449.2 1680.26   459.1 1683.23   470.3 1689.12514.9445 1717.52
#Mann= 6 ,-1 , 0
       0      .1       0  114.12     .06       0  171.24    .045       0
  193.69     .06       0  242.37      .1       0  307.12      .1       0
Bank Sta=171.24,193.69
XS Rating Curve= 0 ,0
Exp/Cntr(USF)=0,0
Exp/Cntr=0.3,0.1

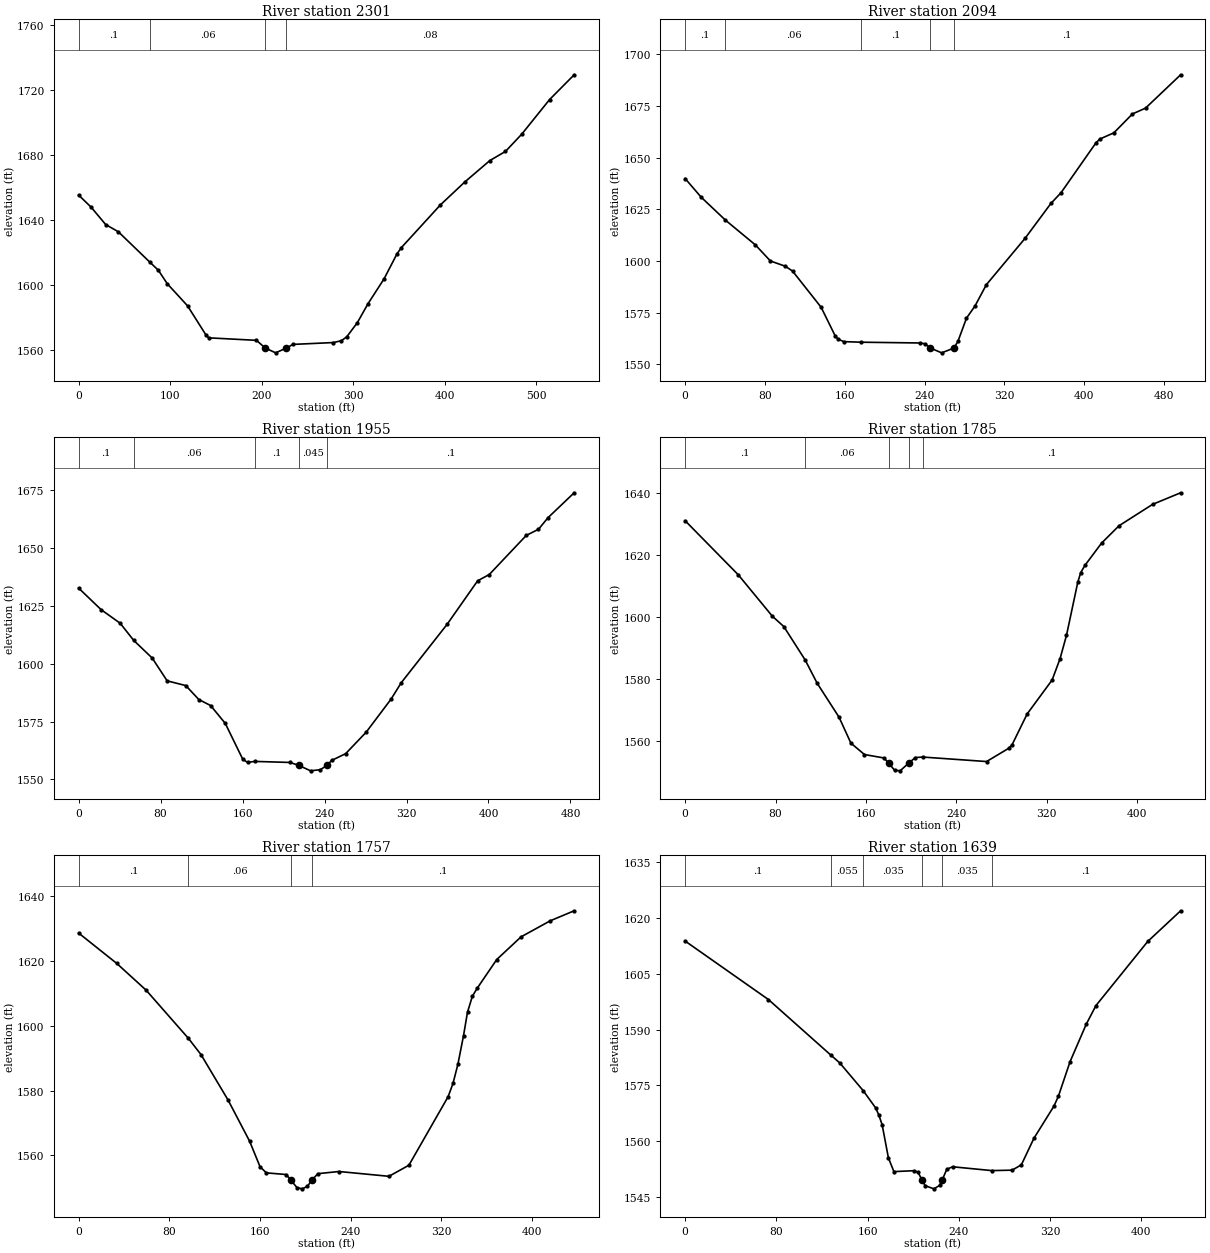
Type RM Length L Ch R = 1 ,2301    ,205.9,207.1,207.9
XS GIS Cut Line= 4
2449597.07445484628579.315020401 2449533.7893915628524.467965514
2449296.68135422628374.271415206 2449148.1724056628278.078118942
#Sta/Elev= 30
       0 1655.41    13.7 1647.93    29.5 1637.28    43.4 1632.79   77.521614.228
    87.1 1609.09    96.8 1600.83     119 1587.16   139.4 1568.95   142.2 1567.45
   194.3 1565.91  203.821561.203   215.2 1558.21  227.08  1561.2   234.1 1563.41
   278.4 1564.55   287.1  1565.7   292.9 1568.07   304.5 1576.81   316.1 1588.44
   333.6 1603.73   347.8 1619.19   352.5    1623   395.3  1649.4   422.1  1663.6
   449.3  1676.7   466.3  1682.3     484 1692.88   514.5 1714.26541.3621 1729.53
#Mann= 4 ,-1 , 0
       0      .1       0   77.52     .06       0  203.82    .045       0
  227.08     .08       0
Bank Sta=203.82,227.08
XS Rating Curve= 0 ,0
Exp/Cntr(USF)=0,0
Exp/Cntr=0.3,0.1

Type RM Length L Ch R = 1 ,2094    ,140.6,139.6,137.8
XS GIS Cut Line= 4
 2449731.2387891628429.1184700942449651.07770888 628369.20861014
2449454.47211213628221.5434623662449325.37058293628143.913784679
#Sta/Elev= 30
       0 1639.97    16.2 1630.88   40.411619.837    70.5 1607.81    85.5 1600.07
   100.5 1597.51   107.7 1595.17   136.3 1577.69   150.5 1563.75   153.4 1562.21
   159.1 1561.05  176.771560.772   235.6  1560.4   240.6 1559.99  245.851557.933
   257.1 1555.63  269.381557.933   273.4 1561.15     282 1572.42   290.5 1578.28
   301.9 1588.59   340.6 1610.97   366.6  1627.9   376.8 1633.13   411.8 1657.27
   415.7 1659.08   429.7 1662.07   448.3  1671.2   461.4 1674.01496.6024 1690.15
#Mann= 5 ,-1 , 0
       0      .1       0   40.41     .06       0  176.77      .1       0
  245.85    .045       0  269.38      .1       0
Bank Sta=245.85,269.38
XS Rating Curve= 0 ,0
Exp/Cntr(USF)=0,0
Exp/Cntr=0.3,0.1

Type RM Length L Ch R = 1 ,1955    ,162.6,169.5,177.1
XS GIS Cut Line= 4
2449813.93127185628328.7061696082449721.11317897628253.607894454
 2449571.7604295628145.6013863682449426.62668426628039.282479971
#Sta/Elev= 30
       0 1632.75      22  1623.4    40.5 1617.56   53.821610.099    71.8 1602.49
    86.4 1592.62   104.6 1590.58   117.3 1584.54   128.8 1581.95   143.1 1574.23
   160.3 1558.62     165 1557.34   171.7 1557.78   206.2 1557.33  214.751556.083
   226.4  1553.7   235.9 1554.21   242.51556.083   246.9  1558.2   260.6 1561.13
   280.6 1570.41     305 1584.78   314.9 1591.85   359.5 1617.01   389.4  1635.9
   400.8 1638.63   436.9 1655.55   448.8 1658.19   458.1 1663.21483.6178 1673.98
#Mann= 5 ,-1 , 0
       0      .1       0   53.82     .06       0   171.7      .1       0
  214.75    .045       0   242.5      .1       0
Bank Sta=214.75,242.5
XS Rating Curve= 0 ,0
Exp/Cntr(USF)=0,0
Exp/Cntr=0.5,0.3

Type RM Length L Ch R = 1 ,1785    ,29,28.5,28
XS GIS Cut Line= 4
2449889.87334785628272.171513031 2449814.7750727628174.290615078
2449726.17598403628002.1552428162449686.51734434627887.398327974
#Sta/Elev= 30
       0 1630.94      47 1613.56    77.2 1600.22    87.3 1596.91  106.221586.156
   116.8 1578.69   136.2 1567.74   146.7  1559.4   158.7 1555.74   175.9 1554.64
  180.241552.934   185.3  1550.7   190.2  1550.5  197.651552.934   203.7 1554.78
   210.31554.931   266.7 1553.49   286.3 1557.75   289.3 1558.91   302.6 1568.79
   324.7 1579.72   331.7 1586.56   337.4 1594.07   347.4 1611.17     350 1614.25
   353.7 1616.56   368.4 1623.72   383.9 1629.32   413.5 1636.18 438.386 1639.92
#Mann= 5 ,-1 , 0
       0      .1       0  106.22     .06       0  180.24    .045       0
  197.65     .06       0   210.3      .1       0
#XS Ineff= 2 , 0
          170.08  1554.8  206.75         1554.76
Permanent Ineff=
       F       F
Bank Sta=180.24,197.65
XS Rating Curve= 0 ,0
Exp/Cntr(USF)=0,0
Exp/Cntr=0.5,0.3

Type RM Length L Ch R = 1 ,1757    ,119.3,117.7,116.2
XS GIS Cut Line= 4
2449924.46918247628256.9830978322449838.40149634628151.507992279
2449748.95860683627998.7800394382449704.23716208627883.179323752
#Sta/Elev= 30
       0 1628.51    33.7 1619.13    59.5 1610.92    96.81596.082   107.9 1591.08
   131.8 1577.07   150.8 1564.39     160 1556.52   165.6 1554.63   183.1 1554.12
   187.31552.346   192.5 1550.12   197.1 1549.71   201.7 1550.44  205.621552.345
     211 1554.38   229.6 1555.05   273.7 1553.57   291.3 1556.98   325.9  1578.1
   330.2 1582.19   334.5 1588.05   339.5 1596.94     343 1604.15   347.3 1609.05
   351.6 1611.54   368.8 1620.36   390.2 1627.33   415.9 1632.27437.0755 1635.37
#Mann= 4 ,-1 , 0
       0      .1       0    96.8     .06       0   187.3    .045       0
  205.62      .1       0
Bank Sta=187.3,205.62
XS Rating Curve= 0 ,0
Exp/Cntr(USF)=0,0
Exp/Cntr=0.5,0.3

Type RM Length L Ch R = 1 ,1639    ,120.9,121.2,121.4
XS GIS Cut Line= 4
2450026.56908465628199.6046404112449959.90881794628100.036140769
2449804.64946256627908.4933490852449753.17761105627863.771904331
#Sta/Elev= 30
       0 1613.79    73.1 1598.06  127.531583.208   135.7 1581.01  156.141573.591
     167 1568.99   169.8 1567.11   172.8 1564.42   178.3 1555.51   183.1 1551.82
   201.1 1552.07   204.3 1551.63  207.981549.456   210.6 1548.03   218.2 1547.19
   223.3 1548.13  225.311549.457   229.5 1552.45   234.6 1553.12  268.991552.091
   286.8 1552.21   294.9 1553.65   305.9 1560.77   323.4 1569.39   327.3 1572.01
   337.6 1581.37   351.8 1591.44   360.3 1596.44   405.7 1613.67434.5735 1621.92
#Mann= 6 ,-1 , 0
       0      .1       0  127.53    .055       0  156.14    .035       0
  207.98    .045       0  225.31    .035       0  268.99      .1       0
Bank Sta=207.98,225.31
XS Rating Curve= 0 ,0
Exp/Cntr(USF)=0,0
Exp/Cntr=0.3,0.1