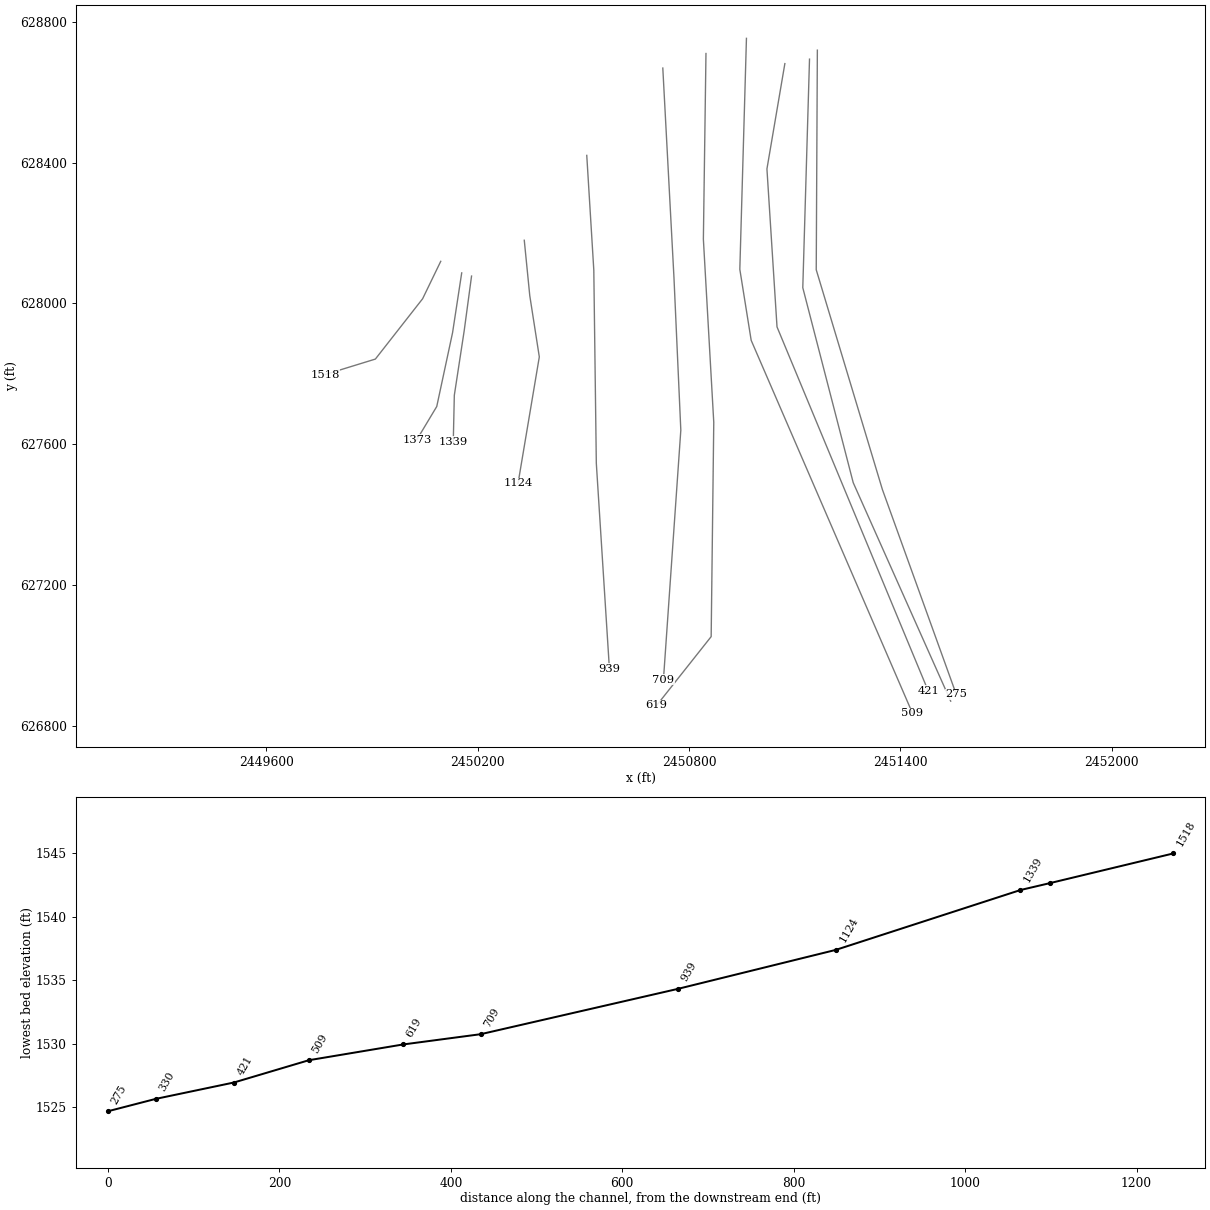
HEC-RAS study HAMMERRN.prj: HAMMERRN

--- HAMMERRN.g01 (geometry) --- (continued)

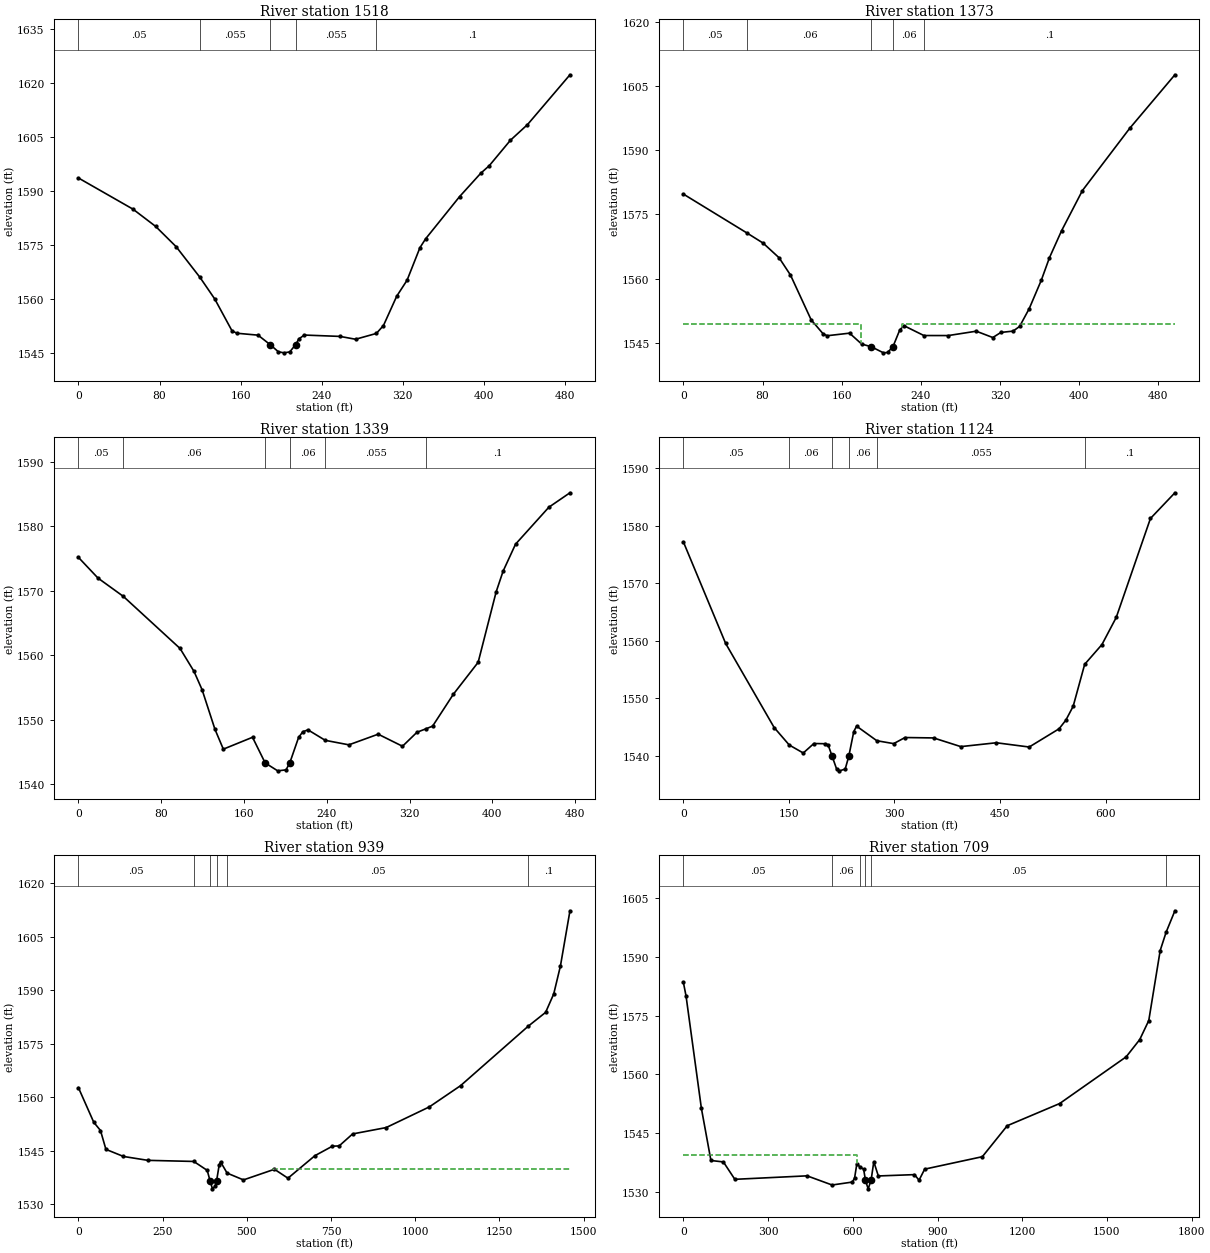
Type RM Length L Ch R = 1 ,1518    ,138.3,144.3,150.1
XS GIS Cut Line= 4
2450094.91695305628119.4435601912450043.44510154628013.124653794
2449909.28076727627841.8330823762449766.67842457627797.955438466
#Sta/Elev= 30
       0 1593.64    53.9 1584.95    76.2 1580.16    96.4 1574.52  119.951565.959
   134.5 1559.96   151.6 1551.06   156.5 1550.43   177.2  1549.9  189.261547.236
   197.2 1545.28   202.8 1544.98   208.5 1545.24  214.171547.235   217.5 1548.87
   222.8 1549.93   258.1 1549.55   273.4 1548.76  293.921550.381   300.9 1552.57
     314 1560.74   324.2 1565.18   336.9 1574.24   342.5 1576.71     376 1588.45
   396.9 1594.96   405.3 1597.06   426.2 1604.15     443 1608.49484.9028 1622.36
#Mann= 5 ,-1 , 0
       0     .05       0  119.95    .055       0  189.26    .045       0
  214.17    .055       0  293.92      .1       0
Bank Sta=189.26,214.17
XS Rating Curve= 0 ,0
Exp/Cntr(USF)=0,0
Exp/Cntr=0.5,0.3

Type RM Length L Ch R = 1 ,1373    ,33.7,34.2,34.7
XS GIS Cut Line= 4
2450154.48530907628086.582442957 2450128.5208074627916.814547417
2450083.58224682627707.1012646922450026.66007008627612.230970126
#Sta/Elev= 30
       0 1579.76   64.681570.604    80.6  1568.3    96.8 1564.86   108.3 1560.82
   129.2 1550.35   141.3 1547.08   145.4 1546.64     168 1547.24   180.2  1544.7
   190.1 1544.05   202.3 1542.64   206.4 1542.72   211.9  1544.1   218.7 1547.95
   222.8 1549.01  243.141546.686   267.8 1546.68   296.1  1547.7   312.8 1546.22
     321 1547.41   333.3 1547.72   339.9 1548.81   349.6 1552.96   361.9 1559.65
   370.1 1564.89   382.3 1571.17   403.4 1580.58   451.1  1595.1   496.9 1607.65
#Mann= 5 ,-1 , 0
       0     .05       0   64.68     .06       0   190.1    .045       0
   211.9     .06       0  243.14      .1       0
#XS Ineff= 2 , 0
             1801549.382     221        1549.382
Permanent Ineff=
       F       F
Bank Sta=190.1,211.9
XS Rating Curve= 0 ,0
Exp/Cntr(USF)=0,0
Exp/Cntr=0.5,0.3

Type RM Length L Ch R = 1 ,1339    ,210.5,215.5,218.6
XS GIS Cut Line= 4
 2450182.4470801 628077.594730842450161.47575183627921.807720816
 2450133.5139808627739.0575744412450130.51807676627606.239162048
#Sta/Elev= 30
       0 1575.18    18.9 1571.97   43.381569.135    98.2 1561.06   111.7  1557.5
   119.5 1554.66   131.9 1548.54     140 1545.46   168.2  1547.3   180.4 1543.33
   192.5  1542.1   200.6 1542.25   204.3 1543.38   212.7 1547.27   216.8 1548.16
   221.8 1548.45  238.471546.827   261.3 1546.13   289.6 1547.78   313.1 1545.91
   327.1 1548.08     3361548.628   342.2 1549.03   362.2 1553.96   386.2 1558.92
   403.6 1569.84   410.3 1573.04   422.3 1577.22   454.5 1582.95   474.9 1585.19
#Mann= 6 ,-1 , 0
       0     .05       0   43.38     .06       0   180.4    .045       0
   204.3     .06       0  238.47    .055       0     336      .1       0
Bank Sta=180.4,204.3
XS Rating Curve= 0 ,0
Exp/Cntr(USF)=0,0
Exp/Cntr=0.5,0.3

Type RM Length L Ch R = 1 ,1124    ,186.6,184.5,184.3
XS GIS Cut Line= 4
2450332.17088326628179.2916292832450347.79682482628021.990484211
 2450374.8817902627848.0216681392450314.46148282627488.625012181
#Sta/Elev= 30
       0 1577.19    60.1 1559.53     129 1544.92   150.51541.876   170.4 1540.49
   185.5 1542.14   201.7  1542.1   205.7 1541.91   211.5  1539.9   217.9 1537.67
   221.9 1537.39     230  1537.7  235.061539.899   242.2 1544.22   246.2 1545.16
  274.931542.625   298.9 1542.12     315 1543.18   355.6 1543.11   394.3  1541.6
   444.8 1542.27   491.5 1541.53     534  1544.7   543.6  1546.2     554 1548.61
  570.351555.903   594.9 1559.34   615.2 1564.05   663.8 1581.25  698.58 1585.72
#Mann= 6 ,-1 , 0
       0     .05       0   150.5     .06       0   211.5    .045       0
  235.06     .06       0  274.93    .055       0  570.35      .1       0
Bank Sta=211.5,235.06
XS Rating Curve= 0 ,0
Exp/Cntr(USF)=0,0
Exp/Cntr=0.3,0.1

Type RM Length L Ch R = 1 ,939     ,229.7,229.8,230.5
XS GIS Cut Line= 4
 2450509.6564293628420.3026652352450529.66220725628094.494281472
2450536.80712794627545.7643719752450573.96071557626962.738843136
#Sta/Elev= 30
       0 1562.66    45.5 1552.97    65.5 1550.66    81.6 1545.38   133.7 1543.39
   206.2  1542.3  342.471541.994   382.4 1539.49  390.791536.568     398 1534.32
   406.1 1535.08  410.181536.567     418 1541.04     422 1541.88  441.391538.732
     490 1536.82     582  1539.8   622.1  1537.3   702.2 1543.61   754.1 1546.27
   774.1 1546.34   814.1  1549.7   913.6 1551.48  1041.8 1557.27  1134.6 1563.22
 1336.111579.929  1387.1 1583.75  1411.2 1588.91  1431.2 1596.791459.407 1612.21
#Mann= 6 ,-1 , 0
       0     .05       0  342.47    .055       0  390.79    .045       0
  410.18    .055       0  441.39     .05       0 1336.11      .1       0
#XS Ineff= 2 , 0
                          576.34         1539.74
Permanent Ineff=
       F       F
Bank Sta=390.79,410.18
XS Rating Curve= 0 ,0
Exp/Cntr(USF)=0,0
Exp/Cntr=0.3,0.1

Type RM Length L Ch R = 1 ,709     ,90.3,90.7,90.5
XS GIS Cut Line= 4
2450725.62709391628668.363726752  2450757.382297 628072.07157973
2450776.78825445627639.8479820372450727.39127186626930.648446229
#Sta/Elev= 30
       0  1583.5     9.5    1580    63.8 1551.33    97.6    1538   141.7 1537.63
   182.3 1533.19   438.1 1534.08  526.72 1531.74   598.3 1532.49   606.3  1533.5
   614.3 1537.12  626.341536.309   638.4 1535.77  644.96 1532.91   654.4 1530.76
  664.74 1532.93   674.4 1537.69   690.4 1534.05   818.5 1534.39   834.6 1532.96
   854.6 1535.79  1058.8 1538.97    1147 1546.88  1332.5 1552.54  1568.1 1564.47
  1616.2 1568.88  1648.2 1573.74  1688.6 1591.61  1709.6 1596.291740.714 1601.77
#Mann= 6 ,-1 , 0
       0     .05       0  526.72     .06       0  626.34     .05       0
  644.96    .045       0  664.74     .05       0  1709.6      .1       0
#XS Ineff= 2 , 0
             614  1539.4
Permanent Ineff=
       F       F
Bank Sta=644.96,664.74
XS Rating Curve= 0 ,0
Exp/Cntr(USF)=0,0
Exp/Cntr=0.3,0.1

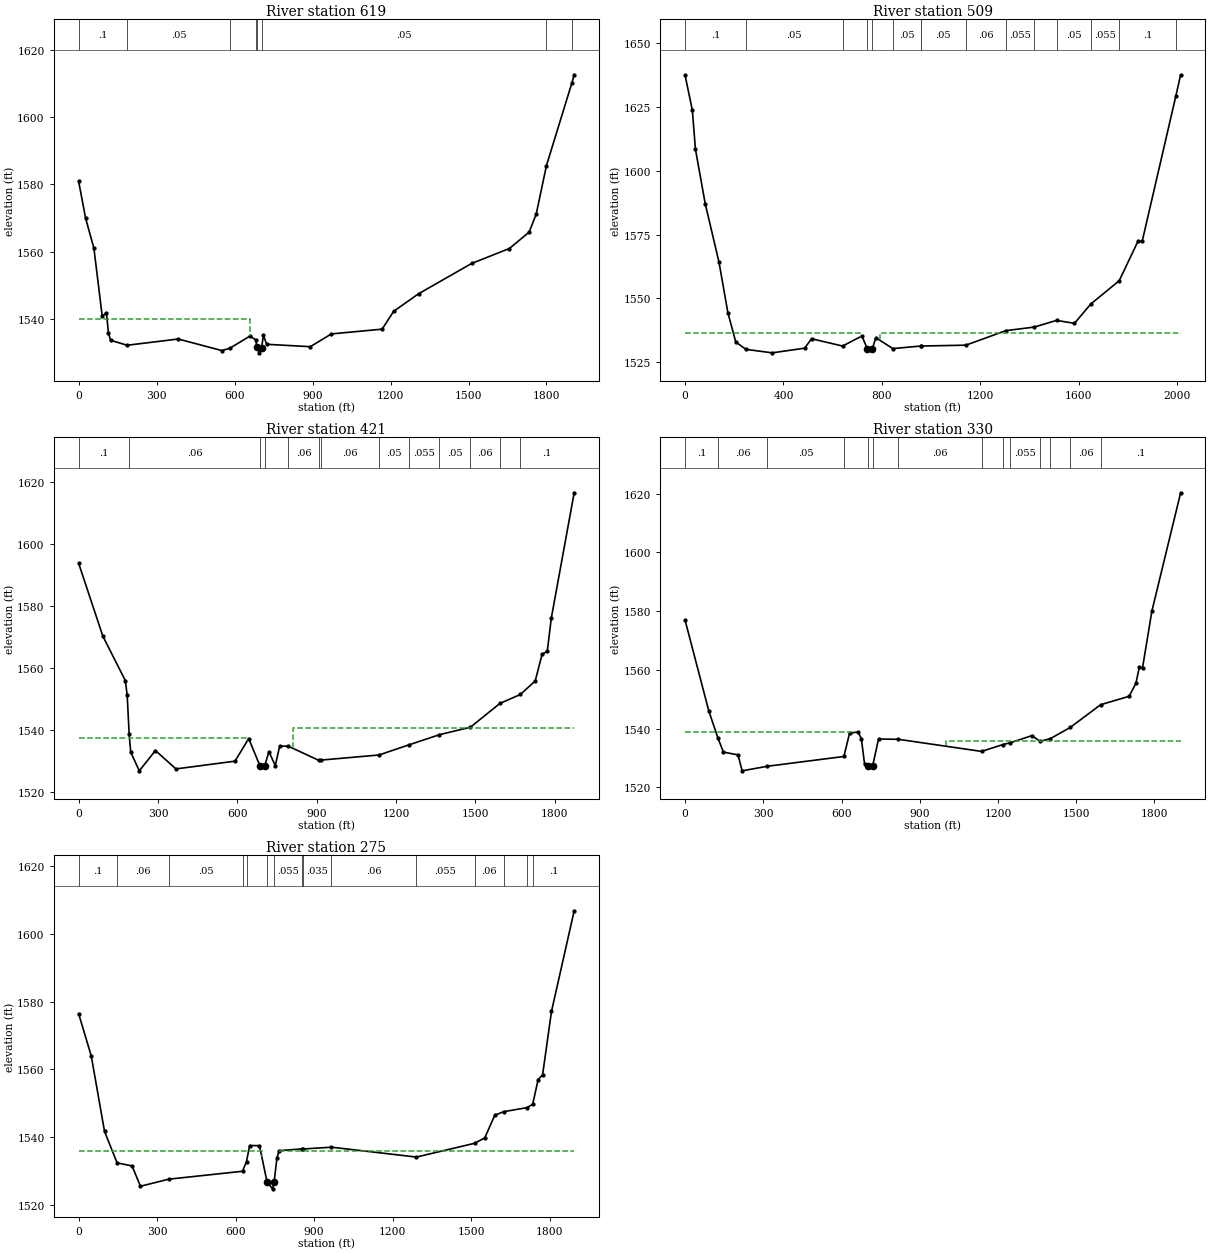
Type RM Length L Ch R = 1 ,619     ,108.4,109.7,111.2
XS GIS Cut Line= 5
2450848.23259948628709.676170779 2450840.8556838628182.226699923
2450870.36334651627662.1541447432450862.98643083627053.558601448
2450708.07120163626858.070336026
#Sta/Elev= 30
       0 1580.92    26.8 1569.97    58.8 1561.01    90.8 1540.82   106.8 1541.85
   114.9  1535.8     123 1533.68  186.781532.205     383 1534.06   550.9 1530.63
  581.45  1531.3     659 1534.93  681.19 1533.82   686.2 1531.63   695.1 1529.95
  703.661531.503   711.1 1535.12   723.2 1532.49   891.4 1531.78   972.2 1535.57
  1167.7 1536.99  1211.7 1542.27  1307.7  1547.5  1511.7  1556.5  1657.1 1560.95
  1733.2 1565.81  1760.5 1571.18 1799.761585.588 1897.111610.0191906.478 1612.58
#Mann= 8 ,-1 , 0
       0      .1       0  186.78     .05       0  581.45     .06       0
  681.19     .05       0   686.2    .045       0  703.66     .05       0
 1799.76      .1       0 1897.11     .05       0
#XS Ineff= 2 , 0
             660 1539.97
Permanent Ineff=
       F       F
Bank Sta=686.2,703.66
XS Rating Curve= 0 ,0
Exp/Cntr(USF)=0,0
Exp/Cntr=0.5,0.3

Type RM Length L Ch R = 1 ,509     ,89.2,87.5,86.3
XS GIS Cut Line= 4
2450963.19445338628752.7831775332450944.37225303628096.695051114
 2450976.6388822627895.0286188132451434.92917803626835.558010287
#Sta/Elev= 30
       01637.324  29.508 1623.67   41.911608.491  81.9261587.043 137.949 1564.15
 173.9641544.435 205.9771532.954  247.141530.082 354.0381528.714 486.0921530.535
 514.1041534.232  640.361531.377 718.9481535.305   741.2 1530.23  761.45 1530.27
 775.6611534.645  844.691530.379   957.51531.373  957.991531.372 1141.831531.718
 1303.861537.392 1419.151538.793  1510.51541.4161583.3041540.258 1649.721547.837
 1765.011556.9241841.3321572.3551858.7651572.443 1995.591629.2832014.9331637.549
#Mann= 15 ,-1 , 0
       0      .1       0  247.14     .05       0  640.36     .06       0
   741.2    .045       0  761.45    .055       0  844.69     .05       0
   957.5     .06       0  957.99     .05       0 1141.83     .06       0
 1303.86    .055       0 1419.15     .06       0  1510.5     .05       0
 1649.72    .055       0 1765.01      .1       0 1995.59      .1       0
#XS Ineff= 2 , 0
             711 1536.67     791         1536.67
Permanent Ineff=
       F       F
Bank Sta=741.2,761.45
XS Rating Curve= 0 ,0
Exp/Cntr(USF)=0,0
Exp/Cntr=0.5,0.3

Type RM Length L Ch R = 1 ,421     ,89.8,91.3,94.5
XS GIS Cut Line= 4
 2451072.2960453628680.9958495272451021.37948903628381.861081436
2451050.02005194627933.1589292982451479.62849547626898.916380046
#Sta/Elev= 30
       0 1593.94    91.4 1570.44   176.6 1556.06   183.5 1551.32  191.021538.772
   196.9 1532.99   229.4 1526.96   290.2 1533.52   367.8 1527.58     591 1530.08
   642.8 1537.38   686.2 1528.39   703.1 1528.55   719.3 1533.15   743.3 1528.63
   759.8 1534.96  792.661534.898  906.911530.384  914.881530.419 1135.411532.078
 1249.661535.379 1363.911538.626 1480.821541.032 1592.421548.719 1669.471551.594
  1725.7 1555.95  1751.7 1564.56  1771.3 1565.54  1786.6 1576.271872.973 1616.68
#Mann= 13 ,-1 , 0
       0      .1       0  191.02     .06       0   686.2    .045       0
   703.1    .055       0  792.66     .06       0  906.91     .05       0
  914.88     .06       0 1135.41     .05       0 1249.66    .055       0
 1363.91     .05       0 1480.82     .06       0 1592.42    .055       0
 1669.47      .1       0
#XS Ineff= 2 , 0
          637.78 1537.45  810.51         1540.86
Permanent Ineff=
       F       F
Bank Sta=686.2,703.1
XS Rating Curve= 0 ,0
Exp/Cntr(USF)=0,0
Exp/Cntr=0.5,0.3

Type RM Length L Ch R = 1 ,330     ,55.8,55.6,57.3
XS GIS Cut Line= 4
2451142.30631018628693.7249885952451123.21260157628044.538896141
2451266.41541609627490.8213466952451543.27419081626870.275817144
#Sta/Elev= 30
       0 1576.92    90.9 1546.07  126.071536.806   146.9 1532.05   202.9  1531.1
   218.9 1525.67   314.31527.213  609.191530.558   631.1 1538.56   663.6 1538.88
     676 1536.66   688.4 1528.05   699.7 1527.22   719.51527.415   742.1 1536.51
  818.381536.401 1137.031532.284 1219.981534.635 1245.291535.163  1330.6 1537.67
 1361.411535.716 1401.481536.647 1477.541540.443 1593.671548.168  1703.2 1551.04
  1729.4 1555.49  1742.5 1560.97  1754.7 1560.71  1790.7  1580.11900.908 1620.32
#Mann= 14 ,-1 , 0
       0      .1       0  126.07     .06       0   314.3     .05       0
  609.19     .06       0   699.7    .045       0   719.5    .055       0
  818.38     .06       0 1137.03     .05       0 1219.98     .06       0
 1245.29    .055       0 1361.41     .05       0 1401.48    .055       0
 1477.54     .06       0 1593.67      .1       0
#XS Ineff= 2 , 0
          637.78 1538.93    1000         1535.79
Permanent Ineff=
       F       F
Bank Sta=699.7,719.5
XS Rating Curve= 0 ,0
Exp/Cntr(USF)=0,0
Exp/Cntr=0.5,0.3

Type RM Length L Ch R = 1 ,275     ,217,217,217
XS GIS Cut Line= 4
2451164.58230354 628719.183266732451161.40001878628095.455452412
2451349.15482003627471.7276380942451559.18561464626889.369525745
#Sta/Elev= 30
       0 1576.42    48.3 1563.93      99 1541.65     147 1532.37   204.3 1531.46
   236.3 1525.46  344.251527.552  626.54 1529.89  641.711532.771   653.6 1537.49
   691.2 1537.45   720.4  1526.7   741.3  1524.7  747.371526.813     758 1533.81
   766.5 1535.96   853.41536.513  857.971536.468  966.111537.002 1290.941534.082
 1513.251538.144  1552.4 1539.75  1590.7 1546.44  1624.41547.486 1713.15 1548.67
 1735.551549.665  1756.5 1556.98  1773.5 1558.37  1807.5  1577.11894.185 1606.82
#Mann= 15 ,-1 , 0
       0      .1       0     147     .06       0  344.25     .05       0
  626.54     .06       0  641.71    .055       0   720.4    .045       0
  747.37    .055       0   853.4     .06       0  857.97    .035       0
  966.11     .06       0 1290.94    .055       0 1513.25     .06       0
  1624.4      .1       0 1713.15    .055       0 1735.55      .1       0
#XS Ineff= 2 , 0
             7001535.982     767        1535.982
Permanent Ineff=
       F       F
Bank Sta=720.4,747.37
XS Rating Curve= 0 ,0
Exp/Cntr(USF)=0,0
Exp/Cntr=0.5,0.3
LCMann Table=0

Chan Stop Cuts=-1
Use User Specified Reach Order=0
Composite Channel Slope=5